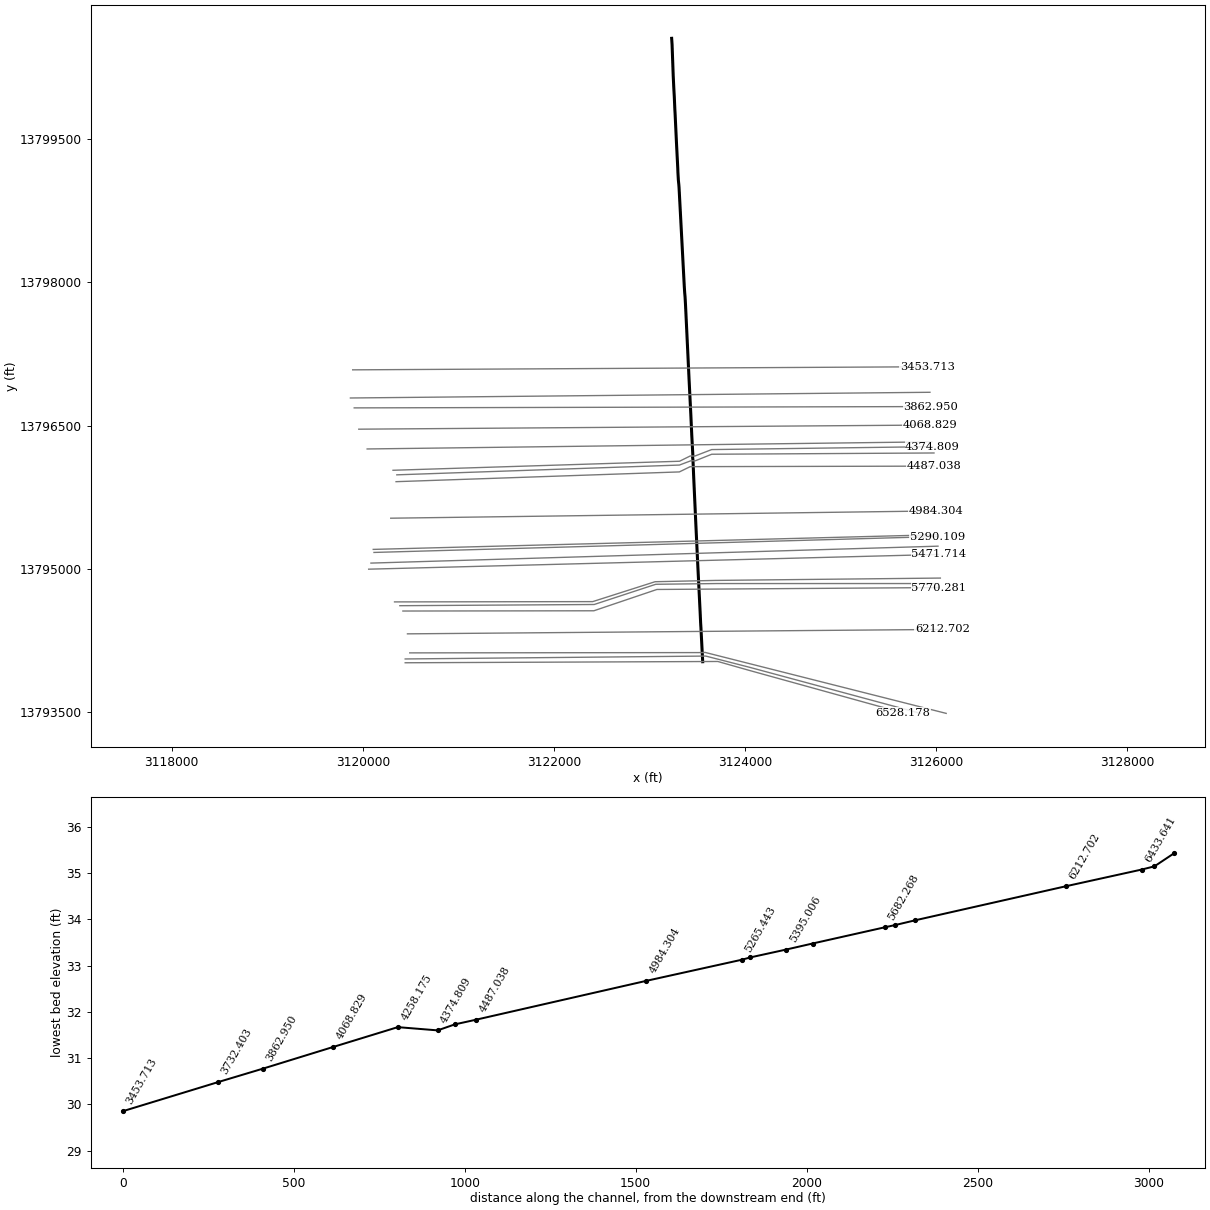
--- C127-00-00.prj (project) ---

Proj Title=C127-00-00
Current Plan=p01
Default Exp/Contr=0.3,0.1
English Units
Geom File=g01
Flow File=f01
Flow File=f02
Plan File=p01
Plan File=p02
Y Axis Title=Elevation
X Axis Title(PF)=Main Channel Distance
X Axis Title(XS)=Station
BEGIN DESCRIPTION:
Sims Bayou Watershed
C127-00-00
HCFCD C127-00-00
Flood Hazard Model
10, 2, 1, 0.2 % Events
Filename C127-00-00.prj
Prepared by:  PSS, SEW  Date:  6-26-03
Reviewed by: #####  Date:  #####
Status Final HEC-RAS
END DESCRIPTION:
DSS File=dss
DSS Export Rating Curves= 0
DSS Export Rating Curve Sorted= 0
DSS Export Volume Flow Curves= 0
DXF OffsetX= 0
DXF OffsetY= 0
DXF ScaleX= 1
DXF ScaleY= 10

--- C127-00-00.p01 (plan) ---

Plan Title=Effective Multi-Profile 2015
Program Version=4.10
Short Identifier=RiskMAP MP
Geom File=g01
Flow File=f01
Subcritical Flow
K Sum by GR= 0
Std Step Tol= 0.01
Critical Tol= 0.01
Num of Std Step Trials= 20
Max Error Tol= 0.3
Flow Tol Ratio= 0.001
Split Flow NTrial= 30
Split Flow Tol= 0.02
Split Flow Ratio= 0.02
Log Output Level= 0
Friction Slope Method= 1
Unsteady Friction Slope Method= 2
Unsteady Bridges Friction Slope Method= 1
Parabolic Critical Depth
Global Vel Dist= 0 , 0 , 0
Global Log Level= 0
CheckData=True
Encroach Param=-1 ,0,0, 2
BEGIN DESCRIPTION:
FEMA Effective Risk Map Study Multi-Profile May 02, 2019
END DESCRIPTION:
Computation Interval=1HOUR
Output Interval=1HOUR
Run HTab= 0
Run UNet= 0
Run PostProcess= 0
Run WQNet= 0
UNET Theta= 1
UNET Theta Warmup= 1
UNET ZTol= 0.02
UNET ZSATol= 0.05
UNET MxIter= 20
UNET MaxInSteps= 1
UNET DtIC= 0
UNET DtMin= 0
UNET MaxCRTS= 20
UNET WFStab= 2
UNET SFStab= 1
UNET WFX= 1
UNET SFX= 1
UNET DSS MLevel= 4
UNET DZMax Abort= 100
UNET Convert EG Bridges=-1
UNET Use Existing IB Tables=-1
UNET Froude Reduction=False
UNET Froude Limit= 1
UNET Froude Power= 10
UNET Time Slicing=0,0, 5
UNET Junction Losses=0
Instantaneous Interval=1HOUR
DSS File=dss
Write IC File= 0
IC Time=0,,
Write IC File at Sim End=0
Echo Input=False
Echo Parameters=False
Echo Output=False
Write Detailed= 0
WQ AD Non Conservative
WQ ULTIMATE=-1
WQ Max Comp Step=1HOUR
WQ Output Interval=15MIN
WQ Output Selected Increments= 0
WQ Output face flow=0
WQ Output face velocity=0
WQ Output face area=0
WQ Output face dispersion=0
WQ Output cell volume=0
WQ Output cell surface area=0
WQ Output cell continuity=0
WQ Output cumulative cell continuity=0
WQ Output face conc=0
WQ Output face dconc_dx=0
WQ Output face courant=0
WQ Output face peclet=0
WQ Output face adv mass=0
WQ Output face disp mass=0
WQ Output cell mass=0
WQ Output cell source sink temp=0
WQ Output cell source sink nsm=0
WQ Output MaxMinRange=-1
WQ Daily Max Min Mean=-1
WQ Daily Range=0
WQ Daily Time=0
WQ Create Restart=0
WQ Fixed Restart=0
WQ System Summary=0
WQ Use Fixed Temperature=0
Sorting and Armoring Iterations= 10
XS Update Threshold= 0.02
Hydraulics Update Threshold= 0.02
Energy Slope Method= 1
Volume Change Method= 0
XS Weighting Method= 0
Number of US Weighted Cross Sections= 1
Number of DS Weighted Cross Sections= 1
Upstream XS Weight=0.25
Main XS Weight=0.5
Downstream XS Weight=0.25
Number of DS XS's Weighted with US Boundary= 1
Upstream Boundary Weight= 1
Weight of XSs Associated with US Boundary= 0
Number of US XS's Weighted with DS Boundary= 1
Downstream Boundary Weight= 0.5
Weight of XSs Associated with DS Boundary= 0.5
Sediment Output Level= 4
Mass or Volume Output= 0
Output Increment Type= 1
Profile and TS Output Increment= 10
XS Output Flag= 0
XS Output Increment= 10
Disregard all LS=0
Disregard all Conn=0
Disregard all Breaches=0
Disregard all Pumps=0

--- C127-00-00.p02 (plan) ---

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Plan Title=Effective Floodway 2015
Short Identifier=RiskMAP FW
Geom File=g01
Flow File=f02
Encroach River=C127-00-00
Encroach Reach=1
Encroach Node=6528.178
       1 3082.95 3136.48
Encroach Node=6471.260
       1 3082.95 3136.48
Encroach Node=6434
       4       1
Encroach Node=6433.641
       1 3033.16 3086.85
Encroach Node=6212.702
       1 3046.02 3100.75
Encroach Node=5770.281
       1 3108.67 3165.46
Encroach Node=5713.559
       1 3135.03 3191.78
Encroach Node=5683
       4       1
Encroach Node=5682.268
       1 3187.85 3245.01
Encroach Node=5471.714
       1 3417.12  3475.3
Encroach Node=5395.006
       1 3390.04 3448.57
Encroach Node=5290.109
       1 3353.13 3415.93
Encroach Node=5266
       4       1
Encroach Node=5265.443
       1 3359.75 3418.93
Encroach Node=4984.304
       1 3162.96 3223.55
Encroach Node=4487.038
       1 3099.37 3162.45
Encroach Node=4425.696
       1 3084.08 3148.43
Encroach Node=4375
       4       1
Encroach Node=4374.809
       1  3116.8 3173.15
Encroach Node=4258.175
       1  3379.6 3431.56
Encroach Node=4068.829
       1 3456.27 3512.75
Encroach Node=3862.950
       1  3492.6 3549.78
Encroach Node=3732.403
       1 3524.79 3582.97
Encroach Node=3453.713
       1 3484.97 3544.57
Encroach Node=2812.698
       1 1969.85 2032.66
Encroach Node=2707.395
       1 1540.11 1590.55
Encroach Node=2647
       4       1
Encroach Node=2646.458
       1 1532.54 1577.21
Encroach Node=2363.951
       1 1511.26 1587.27
Encroach Node=1703.301
       1 1512.16 1573.85
Encroach Node=1604.434
       1 1512.84 1574.51
Encroach Node=1538
       4       1
Encroach Node=1537.664
       1 1494.59 1556.29
Encroach Node=1211.083
       1 1481.39 1552.29
Encroach Node=455.852
       1  916.38 1017.09
Encroach Node=345.842
       1  879.35  986.17
Encroach Node=229
       4       1
Encroach Node=228.634
       1  851.96  921.36
Encroach Node=161.597
       1  813.76  878.71
Encroach Node=138.547
       1  432.87  497.16
Encroach Node=114.735
       1  436.77  500.51
Encroach Node=99
       4       1
Encroach Node=98.021
       1  425.09  499.52
Encroach Node=60.131
       1  399.23  506.31
Encroach Reach=C127-00-00_0001
Encroach Node=6528.178
       1 3082.95 3136.48
Encroach Node=6471.260
       1 3082.95 3136.48
Encroach Node=6434
       4       1
Encroach Node=6433.641
       1 3033.16 3086.85
Encroach Node=6212.702
       1 3046.02 3100.75
Encroach Node=5770.281
       1 3108.67 3165.46
Encroach Node=5713.559
       1 3135.03 3191.78
Encroach Node=5683
       4       1
Encroach Node=5682.268
       1 3187.85 3245.01
Encroach Node=5471.714
       1 3417.12  3475.3
Encroach Node=5395.006
       1 3390.04 3448.57
Encroach Node=5290.109
       1 3353.13 3415.93
Encroach Node=5266
       4       1
Encroach Node=5265.443
       1 3359.75 3418.93
Encroach Node=4984.304
       1 3162.96 3223.55
Encroach Node=4487.038
       1 3099.37 3162.45
Encroach Node=4425.696
       1 3084.08 3148.43
Encroach Node=4375
       4       1
Encroach Node=4374.809
       1  3116.8 3173.15
Encroach Node=4258.175
       1  3379.6 3431.56
Encroach Node=4068.829
       1 3456.27 3512.75
Encroach Node=3862.950
       1  3492.6 3549.78
Encroach Node=3732.403
       1 3524.79 3582.97
Encroach Node=3453.713
       1 3484.97 3544.57
Encroach Node=2812.698
       1 1969.85 2032.66
Encroach Node=2707.395
       1 1540.11 1590.55
Encroach Node=2647
       4       1
Encroach Node=2646.458
       1 1532.54 1577.21
Encroach Node=2363.951
       1 1511.26 1587.27
Encroach Node=1703.301
       1 1512.16 1573.85
Encroach Node=1604.434
       1 1512.84 1574.51
Encroach Node=1538
       4       1
Encroach Node=1537.664
       1 1494.59 1556.29
Encroach Node=1211.083
       1 1481.39 1552.29
Encroach Node=455.852
       1  916.38 1017.09
Encroach Node=345.842
       1  879.35  986.17
Encroach Node=229
       4       1
Encroach Node=228.634
       1  851.96  921.36
Encroach Node=161.597
       1  813.76  878.71
Encroach Node=138.547
       1  432.87  497.16
Encroach Node=114.735
       1  436.77  500.51
Encroach Node=99
       4       1
Encroach Node=98.021
       1  425.09  499.52
Encroach Node=60.131
       1  399.23  506.31
FEMA Effective Risk Map Study Floodway May 02, 2019

--- C127-00-00.f01 (steady flow) ---

Flow Title=Effective Multi-Profile 2015
Program Version=4.10
Number of Profiles= 6
Profile Names=10PCT_10yr,4PCT_25yr,2PCT_50yr,1PCT_100yr,1PCT_Plus,0.2PCT_500yr
River Rch & RM=C127-00-00,C127-00-00_0001 ,6528.178
     119     150     179     210     252     298
River Rch & RM=C127-00-00,C127-00-00_0001 ,5290.109
     123     155     184     216     259     307
River Rch & RM=C127-00-00,C127-00-00_0001 ,4258.175
     329     415     494     580     696     825
River Rch & RM=C127-00-00,C127-00-00_0001 ,3732.403
     370     466     555     652     782     927
River Rch & RM=C127-00-00,C127-00-00_0001 ,1604.434
     399     502     598     703     844     999
River Rch & RM=C127-00-00,C127-00-00_0001 ,455.852
     467     588     700     822     986    1169
River Rch & RM=C127-00-00,C127-00-00_0001 ,60.131
     480     604     719     845    1014    1201
Boundary for River Rch & Prof#=C127-00-00,C127-00-00_0001 , 1
Up Type= 0
Dn Type= 4
Dn Rating Curve # Pts= 14
       0   25.32      74    27.9     149   29.42     298   29.81     446   32.34
     595   33.13     744   33.82     893   34.47    1042   35.05    1190   35.69
    1339   36.25    1488   36.67    1637   37.06    1786   37.43
Boundary for River Rch & Prof#=C127-00-00,C127-00-00_0001 , 2
Up Type= 0
Dn Type= 2
Boundary for River Rch & Prof#=C127-00-00,C127-00-00_0001 , 3
Up Type= 0
Dn Type= 2
Boundary for River Rch & Prof#=C127-00-00,C127-00-00_0001 , 4
Up Type= 0
Dn Type= 2
DSS Import GetInterval= 0
DSS Import GetPeak= 0
DSS Import FillOption= 0

--- C127-00-00.f02 (steady flow) ---

Flow Title=Effective Floodway 2015
Program Version=4.10
Number of Profiles= 2
Profile Names=1PCT_100yr,Floodway
River Rch & RM=C127-00-00,C127-00-00_0001 ,6528.178
     210     210
River Rch & RM=C127-00-00,C127-00-00_0001 ,5290.109
     216     216
River Rch & RM=C127-00-00,C127-00-00_0001 ,4258.175
     580     580
River Rch & RM=C127-00-00,C127-00-00_0001 ,3732.403
     652     652
River Rch & RM=C127-00-00,C127-00-00_0001 ,1604.434
     703     703
River Rch & RM=C127-00-00,C127-00-00_0001 ,455.852
     822     822
River Rch & RM=C127-00-00,C127-00-00_0001 ,60.131
     845     845
Boundary for River Rch & Prof#=C127-00-00,C127-00-00_0001 , 1
Up Type= 0
Dn Type= 4
Dn Rating Curve # Pts= 14
       0   25.32      74    27.9     149   29.42     298   29.81     446   32.34
     595   33.13     744   33.82     893   34.47    1042   35.05    1190   35.69
    1339   36.25    1488   36.67    1637   37.06    1786   37.43
Boundary for River Rch & Prof#=C127-00-00,C127-00-00_0001 , 2
Up Type= 0
Dn Type= 0
DSS Import GetInterval= 0
DSS Import GetPeak= 0
DSS Import FillOption= 0

--- C127-00-00.g01 (geometry) ---

Geom Title=C127-00-00 2015
Program Version=4.10

River Reach=C127-00-00      ,C127-00-00_0001
Reach XY= 30
     3123556.232    13794030.607     3123537.605    13794389.546
      3123534.87    13794431.678      3123529.03    13794558.371
     3123503.086    13795075.935     3123483.128    13795499.921
     3123461.914      13795965.3     3123454.818    13796134.421
     3123450.605    13796170.196     3123453.635     13796182.91
     3123441.883    13796400.964     3123432.347    13796610.591
     3123413.794    13796981.209     3123376.614    13797761.473
     3123371.736    13797847.364     3123367.966    13797889.496
     3123363.827    13797952.769     3123309.055    13798987.306
     3123306.911    13799016.281     3123301.663    13799069.057
     3123296.932      13799151.4      3123295.38    13799195.307
     3123281.779    13799461.111     3123267.513    13799763.873
     3123264.926     13799807.78     3123259.087    13799941.273
     3123254.208    13800027.903     3123247.926    13800157.997
     3123235.751    13800489.073     3123231.434    13800551.677

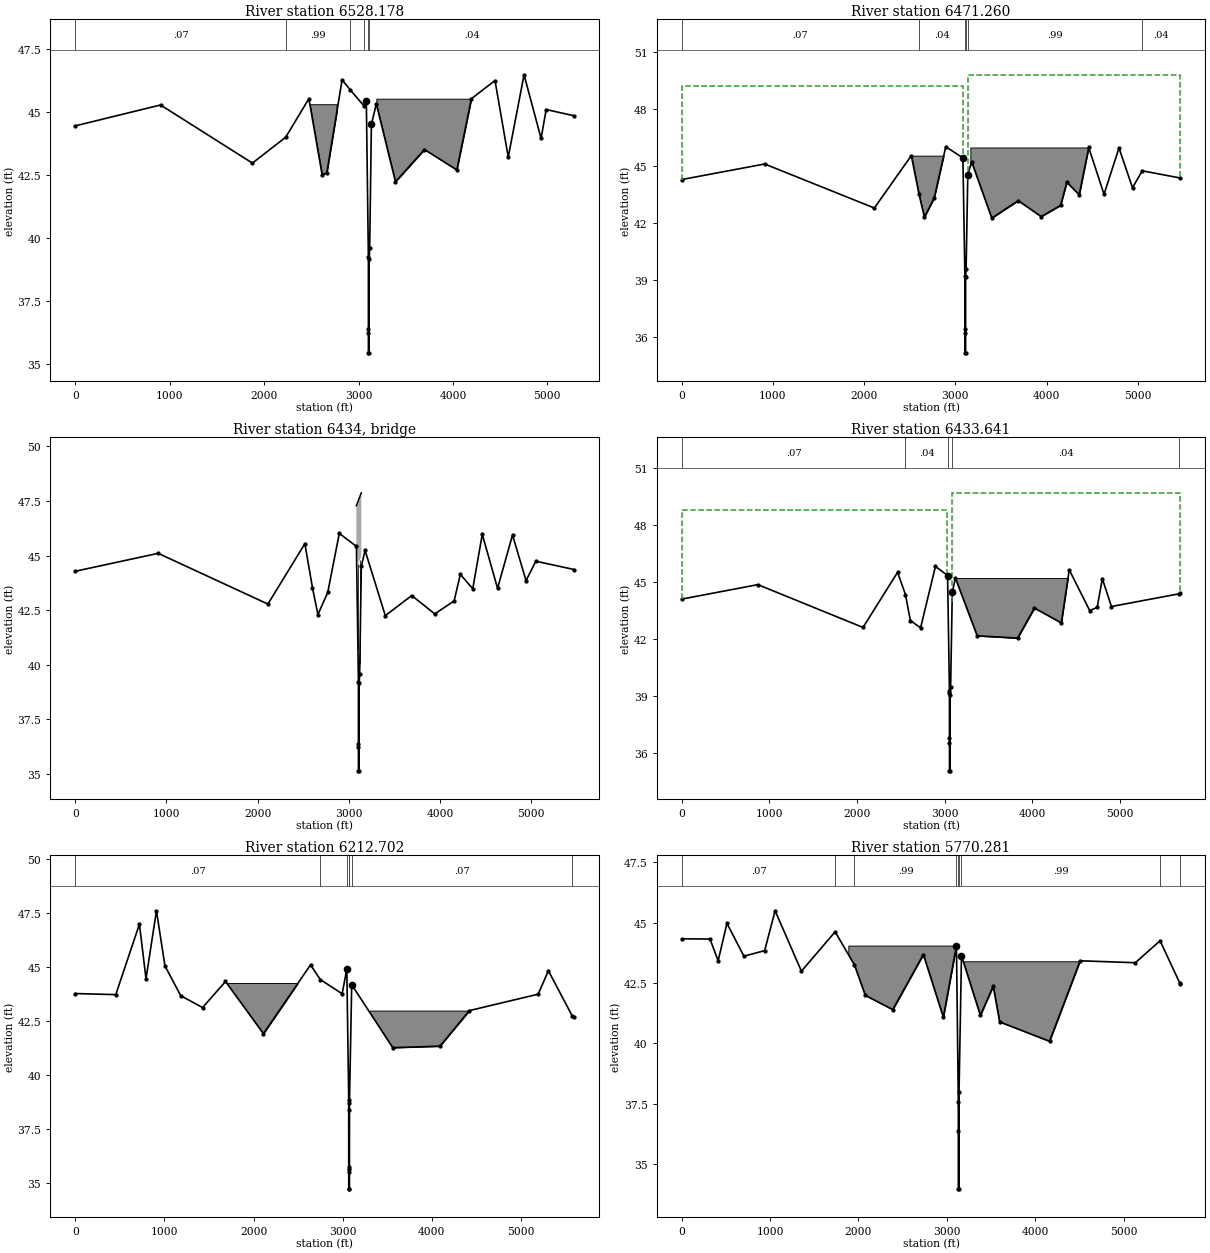
Type RM Length L Ch R = 1 ,6528.178,56.33,56.9,38.24
BEGIN DESCRIPTION:
Bridge Section 4 - US Orem Rd
END DESCRIPTION:
XS GIS Cut Line= 4
     3120443.997    13794019.626     3123714.259    13794033.088
     3124041.395    13793940.316     3125653.112     13793494.18
#Sta/Elev= 30
       0   44.45   902.9   45.28 1876.22   42.97 2229.07      44  2474.3   45.53
 2614.32   42.51 2664.07   42.58 2826.15   46.28 2910.11   45.89 3061.24   45.23
 3082.95   45.42 3104.57   39.22 3104.57   36.38 3104.92   36.22 3104.92   35.43
  3112.8   35.43  3112.9   39.15 3118.14   39.58 3136.48   44.51 3188.74   45.32
  3391.5   42.23 3698.61   43.51 4041.56    42.7 4195.87   45.53 4445.62   46.25
 4586.09   43.21 4753.41   46.48 4933.82   43.95 4987.73    45.1 5282.65   44.85
#Mann= 6 ,-1 , 0
       0     .07       0 2229.07     .99       0 2910.11    .016       0
 3061.24     .04       0 3104.57    .015       0  3112.9     .04       0
#Block Obstruct= 2 ,-1
  2474.3 2767.93   45.31 3188.74 4195.87   45.53
Bank Sta=3082.95,3136.48
XS Rating Curve= 0 ,0
Exp/Cntr=0.5,0.3

Type RM Length L Ch R = 1 ,6471.260,37.67,37.62,37.35
BEGIN DESCRIPTION:
Bridge Section 3 - US Orem Rd
END DESCRIPTION:
XS GIS Cut Line= 4
     3120443.997    13794059.421     3123588.331    13794089.614
     3124045.414     13793972.47     3125833.978     13793490.16
#Sta/Elev= 30
       0   44.28   908.8    45.1 2111.95   42.78 2517.42   45.54 2601.12   43.52
 2660.55    42.3 2768.16   43.31 2895.13   46.01 3082.95   45.42 3104.57   39.22
 3104.57   36.38 3104.92   36.22 3104.92   35.15  3112.8   35.15  3112.9   39.15
 3118.14   39.58 3136.48   44.51 3177.75   45.23 3399.39   42.25 3689.85   43.17
 3941.18   42.33 4154.12   42.92 4222.05   44.14 4358.48   43.48  4462.8   45.97
 4630.36    43.5 4794.34   45.94 4942.97   43.85 5049.44   44.74 5468.79   44.36
#Mann= 6 ,-1 , 0
       0     .07       0 2601.12     .04       0 3104.57    .015       0
  3112.9     .04       0 3136.48     .99       0 5049.44     .04       0
#XS Ineff= 2 , 0
       0    3082    49.2 3135.55       0    49.8
Permanent Ineff=
       F       F
#Block Obstruct= 2 ,-1
 2517.42 2895.13   45.54 3164.79  4462.8   45.97
Bank Sta=3082.95,3136.48
XS Rating Curve= 0 ,0
Exp/Cntr=0.5,0.3

Type RM Length L Ch R = 3 ,6434    ,,,
BEGIN DESCRIPTION:
East Orem Bridge
END DESCRIPTION:
Bridge Culvert--1,0,-1,-1, 0
Deck Dist Width WeirC Skew NumUp NumDn MinLoCord MaxHiCord MaxSubmerge Is_Ogee
0.3,36,2.6,0, 2, 2, , , 0.95, 0, 0,0,,
  3081.7 3136.38
   47.28   47.87
   44.46   44.95
 3030.35 3085.02
   47.92   48.52
   45.15   45.75
Pier Skew, UpSta & Num, DnSta & Num=  ,3099.4, 2 ,3047.54, 2 , 0 , 0 , 0 ,,
     1.3     1.3
       0      48
     1.3     1.3
       0      48
Pier Skew, UpSta & Num, DnSta & Num=  ,3119.92, 2 ,3067.93, 2 , 0 , 0 , 0 ,,
     1.3     1.3
       0      48
     1.3     1.3
       0      48
Abutment Skew #Up #Dn= , 3 , 4
 3075.05    3082    3082
   46.04   49.25   44.47
 3024.25 3024.25  3031.5  3031.5
   44.85      47   49.06    45.1
Abutment Skew #Up #Dn= , 8 , 4
 3135.49 3135.63 3136.64 3138.94 3140.63 3142.55 3142.66 3163.51
   43.76   44.93   49.88   49.84   49.34   47.62   46.47   44.93
    3085    3085 3088.73 3091.86
   41.33    49.7   49.64   47.03
BR Coef= 1 , 1 , 1 ,1.25, 0 ,,,0.8,-1,2,0,
WSPro=,,,, 1 ,,,, 0 ,,,, 0 ,,,,-1 ,-1 ,-1 , 0 , 0 , 0 , 0 , 0
BC Design=,, 0 ,, 0 ,,,,,,
BC HTab HWMax=46.01
BC Use User HTab Curves=0
BC User HTab FreeFlow(D)= 0

Type RM Length L Ch R = 1 ,6433.641,220.85,220.87,240.39
BEGIN DESCRIPTION:
Bridge Section 2 -DS Orem Rd
END DESCRIPTION:
XS GIS Cut Line= 4
     3120491.751    13794123.094     3123512.857    13794126.027
      3123582.82    13794127.516     3126103.267     13793490.16
#Sta/Elev= 30
       0   44.11  868.32   44.87 2068.22   42.62 2462.75   45.52 2552.35   44.35
 2608.87   42.98 2725.38    42.6 2894.86   45.83 3033.16   45.35 3054.54    39.3
  3054.6   39.17  3054.6   36.79 3055.07   36.54 3055.08   35.08 3062.95   35.08
 3063.04   39.08 3068.21    39.5 3086.85   44.46 3122.01   45.22 3370.88   42.18
 3831.93   42.06  4024.6   43.64 4330.95   42.86 4421.41   45.65 4654.61   43.51
 4739.99   43.67 4799.36   45.18 4903.08   43.72  5676.7   44.39 5690.87   44.41
#Mann= 5 ,-1 , 0
       0     .07       0 2552.35     .04       0 3033.16    .015       0
 3086.85     .04       0  5676.7    .016       0
#XS Ineff= 2 , 0
       0  3031.5    48.8    3085       0    49.7
Permanent Ineff=
       F       F
#Block Obstruct= 1 ,-1
 3122.01 4421.41   45.22
Bank Sta=3033.16,3086.85
XS Rating Curve= 0 ,0
Exp/Cntr=0.5,0.3

Type RM Length L Ch R = 1 ,6212.702,442.4,442.45,442.39
BEGIN DESCRIPTION:
Bridge Section 1 - DS Orem Rd
END DESCRIPTION:
XS GIS Cut Line= 2
     3120467.874     13794322.07      3126062.28    13794368.334
#Sta/Elev= 30
       0   43.78  454.13   43.73  719.53      47  793.25   44.47  910.46   47.62
 1005.92   45.06 1183.22   43.68 1428.06   43.13 1685.01   44.34 2110.49   41.92
 2638.63   45.11 2748.79   44.43 2993.75   43.77 3046.02   44.92 3067.31   38.85
 3067.39    38.4  3067.4   35.72 3067.65   35.62 3067.68    35.5 3067.68   34.72
 3075.52   34.72 3075.62   38.72 3100.75   44.19 3560.98   41.27 4090.49   41.34
 4421.16   42.99 5192.52   43.75 5307.09   44.84 5577.42   42.72  5594.6   42.68
#Mann= 7 ,-1 , 0
       0     .07       0 2748.79     .99       0 3046.02     .04       0
 3067.31    .015       0 3075.62     .04       0 3100.75     .07       0
 5577.42    .016       0
#Block Obstruct= 2 ,-1
 1685.01 2492.18   44.27 3124.88 4421.16   42.99
Bank Sta=3046.02,3100.75
XS Rating Curve= 0 ,0
Exp/Cntr=0.3,0.1

Type RM Length L Ch R = 1 ,5770.281,56.25,56.73,57.26
BEGIN DESCRIPTION:
Cross-Section 4:  10" pipeline US
END DESCRIPTION:
XS GIS Cut Line= 4
      3120420.12    13794560.842      3122417.58    13794563.391
     3123077.348    13794786.368      3126027.21    13794806.222
#Sta/Elev= 30
       0   44.33  319.67   44.32  411.86   43.42  511.41   44.97  703.15   43.61
  938.03   43.84 1056.22   45.49 1354.23   42.99 1735.81   44.62 1953.78   43.25
 2076.92   41.99 2387.86    41.4 2734.07   43.68 2960.43   41.08 3108.67   44.05
 3129.75   37.57 3129.83   36.38 3129.84   33.98 3137.64   33.98 3137.73   37.98
 3165.46   43.63 3378.98   41.16  3524.6   42.37 3597.67   40.89 4162.22   40.09
 4508.02   43.42 5133.55   43.34 5412.59   44.25 5635.92    42.5 5643.82   42.44
#Mann= 9 ,-1 , 0
       0     .07       0 1735.81     .04       0 1953.78     .99       0
 3108.67     .04       0 3129.75    .015       0 3137.73     .04       0
 3165.46     .99       0 5412.59     .04       0 5635.92    .016       0
#Block Obstruct= 2 ,-1
 1885.05 3108.67   44.05 3182.32 4502.73    43.4
Bank Sta=3108.67,3165.46
XS Rating Curve= 0 ,0
Exp/Cntr=0.5,0.3

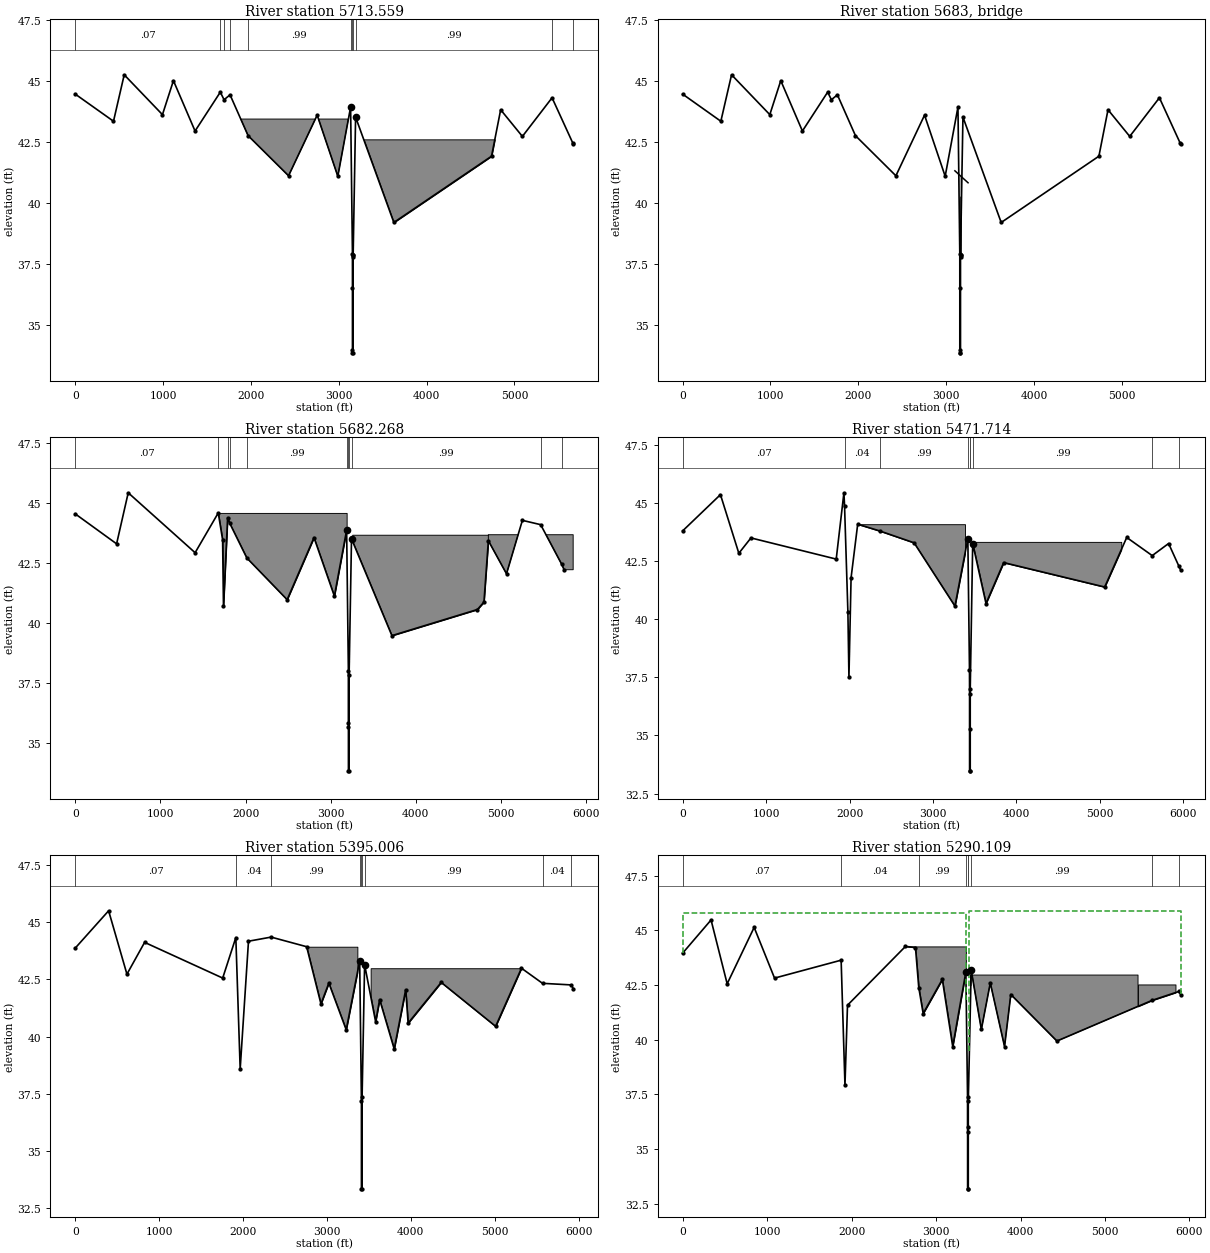
Type RM Length L Ch R = 1 ,5713.559,30.4,31.31,32.3
BEGIN DESCRIPTION:
Cross-Section 3:  10" pipeline US
END DESCRIPTION:
XS GIS Cut Line= 5
     3120388.284    13794616.556     3122420.815    13794629.036
     3123065.763    13794840.659     3123703.153    13794848.217
      3126023.31    13794848.304
#Sta/Elev= 30
       0   44.46  435.44   43.35  557.43   45.25  992.87   43.62 1117.76   45.01
 1364.08   42.95 1651.53   44.54 1694.28   44.23 1762.47   44.43 1968.09   42.76
 2428.53   41.12  2754.5    43.6 2989.49    41.1 3135.03   43.93 3155.98   37.92
 3156.08   36.53 3156.09   34.01 3156.13   33.88 3163.91   33.88 3164.02   37.81
 3164.02   37.88 3164.02   37.89 3191.78   43.52 3627.25   39.21 4739.55   41.92
 4843.45   43.82 5090.75   42.73 5428.63   44.31 5663.16   42.47 5668.94   42.43
#Mann= 11 ,-1 , 0
       0     .07       0 1651.53     .04       0 1694.28     .07       0
 1762.47     .04       0 1968.09     .99       0 3135.03     .04       0
 3155.98    .015       0 3164.02     .04       0 3191.78     .99       0
 5428.63     .04       0 5663.16    .016       0
#Block Obstruct= 2 ,-1
 1875.61 3105.86   43.44 3208.44 4802.37   42.61
Bank Sta=3135.03,3191.78
XS Rating Curve= 0 ,0
Exp/Cntr=0.5,0.3

Type RM Length L Ch R = 3 ,5683    ,,,
BEGIN DESCRIPTION:
10" Pipeline
END DESCRIPTION:
Bridge Culvert--1,0,-1,-1, 0
Deck Dist Width WeirC Skew NumUp NumDn MinLoCord MaxHiCord MaxSubmerge Is_Ogee
0.7,0.8,2.6,0, 2, 2, , , 0.95, 0, 0,0,,
    3100    3250
  41.324  40.834
  40.491  40.001
    3150    3250
  41.324  40.834
  40.491  40.001
Pier Skew, UpSta & Num, DnSta & Num=  ,3155.73, 2 ,3208.06, 2 , 0 , 0 , 0 ,,
      .5      .5
       0    40.5
      .5      .5
       0    40.5
Pier Skew, UpSta & Num, DnSta & Num=  ,3164.27, 2 ,3217.05, 2 , 0 , 0 , 0 ,,
      .5      .5
       0    40.5
      .5      .5
       0    40.5
BR Coef=-1 , 1 , 1 ,1.25, 0 ,,,0.8,-1,2,0,
WSPro=,,,, 1 ,,,, 0 ,,,, 0 ,,,,-1 ,-1 ,-1 , 0 , 0 , 0 , 0 , 0
BC Design=,, 0 ,, 0 ,,,,,,
BC HTab HWMax=45.25
BC Use User HTab Curves=0
BC User HTab FreeFlow(D)= 0

Type RM Length L Ch R = 1 ,5682.268,210.16,210.56,211.02
BEGIN DESCRIPTION:
Cross-Section 2:  10" pipeline DS
END DESCRIPTION:
XS GIS Cut Line= 5
      3120332.57    13794656.351     3122405.699    13794659.268
     3123058.105    13794867.393     3123685.518    13794880.969
       3126042.4    13794905.572
#Sta/Elev= 30
       0   44.55  485.74    43.3  622.17   45.43 1407.98   42.93 1679.85   44.59
 1730.95   43.47 1741.13    40.7 1789.99   44.39 1815.55   44.15 2015.56   42.71
 2489.14   40.97 2804.45   43.56 3043.77   41.12 3187.85   43.87 3208.31   38.01
 3208.37   35.81 3208.86   35.65 3208.91   33.83 3216.69   33.83  3216.8   37.83
 3245.01   43.51 3719.54   39.47 4723.61   40.56 4800.85   40.87 4852.77   43.43
 5065.87   42.05 5252.22   44.28 5466.86    44.1 5715.16   42.44  5742.5   42.22
#Mann= 11 ,-1 , 0
       0     .07       0 1679.85     .04       0 1789.99     .07       0
 1815.55     .04       0 2015.56     .99       0 3187.85     .04       0
 3208.31    .015       0  3216.8     .04       0 3245.01     .99       0
 5466.86     .04       0 5715.16    .016       0
#Block Obstruct= 3 ,-1
 1679.85 3187.85   44.59 3253.82 4852.77   43.68 4852.22 5848.87   43.68
Bank Sta=3187.85,3245.01
XS Rating Curve= 0 ,0
Exp/Cntr=0.5,0.3

Type RM Length L Ch R = 1 ,5471.714,76.35,76.71,77.12
BEGIN DESCRIPTION:
Cross-Section 1:  10" pipeline DS
END DESCRIPTION:
XS GIS Cut Line= 2
     3120061.962    13794998.591     3126024.891    13795152.731
#Sta/Elev= 30
       0   43.79  453.45   45.35   673.7   42.83  818.87   43.49 1840.34   42.58
 1932.56   45.43 1940.03   44.88 1980.38   40.29 1992.58    37.5 2018.37   41.78
 2097.62   44.08 2361.09   43.79 2773.09   43.28  3262.4   40.56 3417.12   43.46
 3436.78   37.81 3437.89   36.79 3437.97   35.28 3437.98   33.48 3445.75   33.48
 3445.84   37.01  3475.3   43.25 3634.73   40.67 3846.35   42.43 5056.61   41.38
 5320.59   43.51 5626.05   42.73 5822.07   43.25 5942.37    42.3 5964.92   42.12
#Mann= 9 ,-1 , 0
       0     .07       0 1940.03     .04       0 2361.09     .99       0
 3417.12     .04       0 3437.89    .015       0 3445.84     .04       0
  3475.3     .99       0 5626.05     .04       0 5942.37    .016       0
#Block Obstruct= 2 ,-1
 2097.62 3382.76   44.08 3474.63 5254.99   43.32
Bank Sta=3417.12,3475.3
XS Rating Curve= 0 ,0
Exp/Cntr=0.3,0.1

Type RM Length L Ch R = 1 ,5395.006,105.06,104.9,104.76
BEGIN DESCRIPTION:
Bridge Section 4 - US Hickok St
END DESCRIPTION:
XS GIS Cut Line= 2
     3120085.839    13795062.263     3126017.654    13795239.341
#Sta/Elev= 30
       0   43.87  397.69    45.5  616.01   42.73   826.7   44.12 1757.27   42.56
 1913.92   44.33 1965.65   38.59  2064.7   44.17 2334.62   44.35 2757.77   43.93
 2928.28   41.43 3022.46   42.34 3229.48    40.3 3390.04   43.31 3410.71   37.17
 3410.81   33.35 3418.57   33.35 3418.69   37.36 3448.57   43.15 3580.08   40.65
 3627.92   41.62 3801.46   39.46  3938.3   42.05 3967.33   40.59 4361.82   42.37
 5010.35   40.45  5318.3   42.99 5568.95   42.33 5913.98   42.26 5934.46    42.1
#Mann= 9 ,-1 , 0
       0     .07       0 1913.92     .04       0 2334.62     .99       0
 3390.04     .04       0 3410.71    .015       0 3418.69     .04       0
 3448.57     .99       0 5568.95     .04       0 5913.98    .016       0
#Block Obstruct= 2 ,-1
 2757.77 3362.28   43.93 3520.68  5318.3   42.99
Bank Sta=3390.04,3448.57
XS Rating Curve= 0 ,0
Exp/Cntr=0.5,0.3

Type RM Length L Ch R = 1 ,5290.109,24.87,24.66,24.46
BEGIN DESCRIPTION:
Bridge Section 3 - US Hickok St
END DESCRIPTION:
XS GIS Cut Line= 2
     3120117.675     13795173.69     3126009.326    13795339.887
#Sta/Elev= 30
       0   43.96  336.82   45.48  527.58   42.56   846.9   45.14 1088.31   42.82
 1876.65   43.64 1921.97   37.92 1951.98   41.58 2638.14   44.27 2756.48   44.22
 2795.52   42.39 2847.58    41.2 3074.35   42.76 3197.48   39.69 3353.13    43.1
    3373   37.37 3373.03   35.99 3373.74    35.8 3373.81   33.18 3381.58   33.18
  3381.7   37.18 3415.93    43.2 3536.46   40.47 3642.23    42.6 3811.02   39.69
 3885.23   42.07 4431.04   39.94 5555.97    41.8 5875.78   42.21 5893.99   42.07
#Mann= 9 ,-1 , 0
       0     .07       0 1876.65     .04       0 2795.52     .99       0
 3353.13     .04       0    3373    .015       0  3381.7     .04       0
 3415.93     .99       0 5555.97     .04       0 5875.78    .016       0
#XS Ineff= 2 , 0
       0  3357.5    45.8  3394.7       0    45.9
Permanent Ineff=
       F       F
#Block Obstruct= 3 ,-1
 2638.14 3353.13   44.27 3411.76 5390.99   42.96 5390.99 5834.29   42.53
Bank Sta=3353.13,3415.93
XS Rating Curve= 0 ,0
Exp/Cntr=0.5,0.3

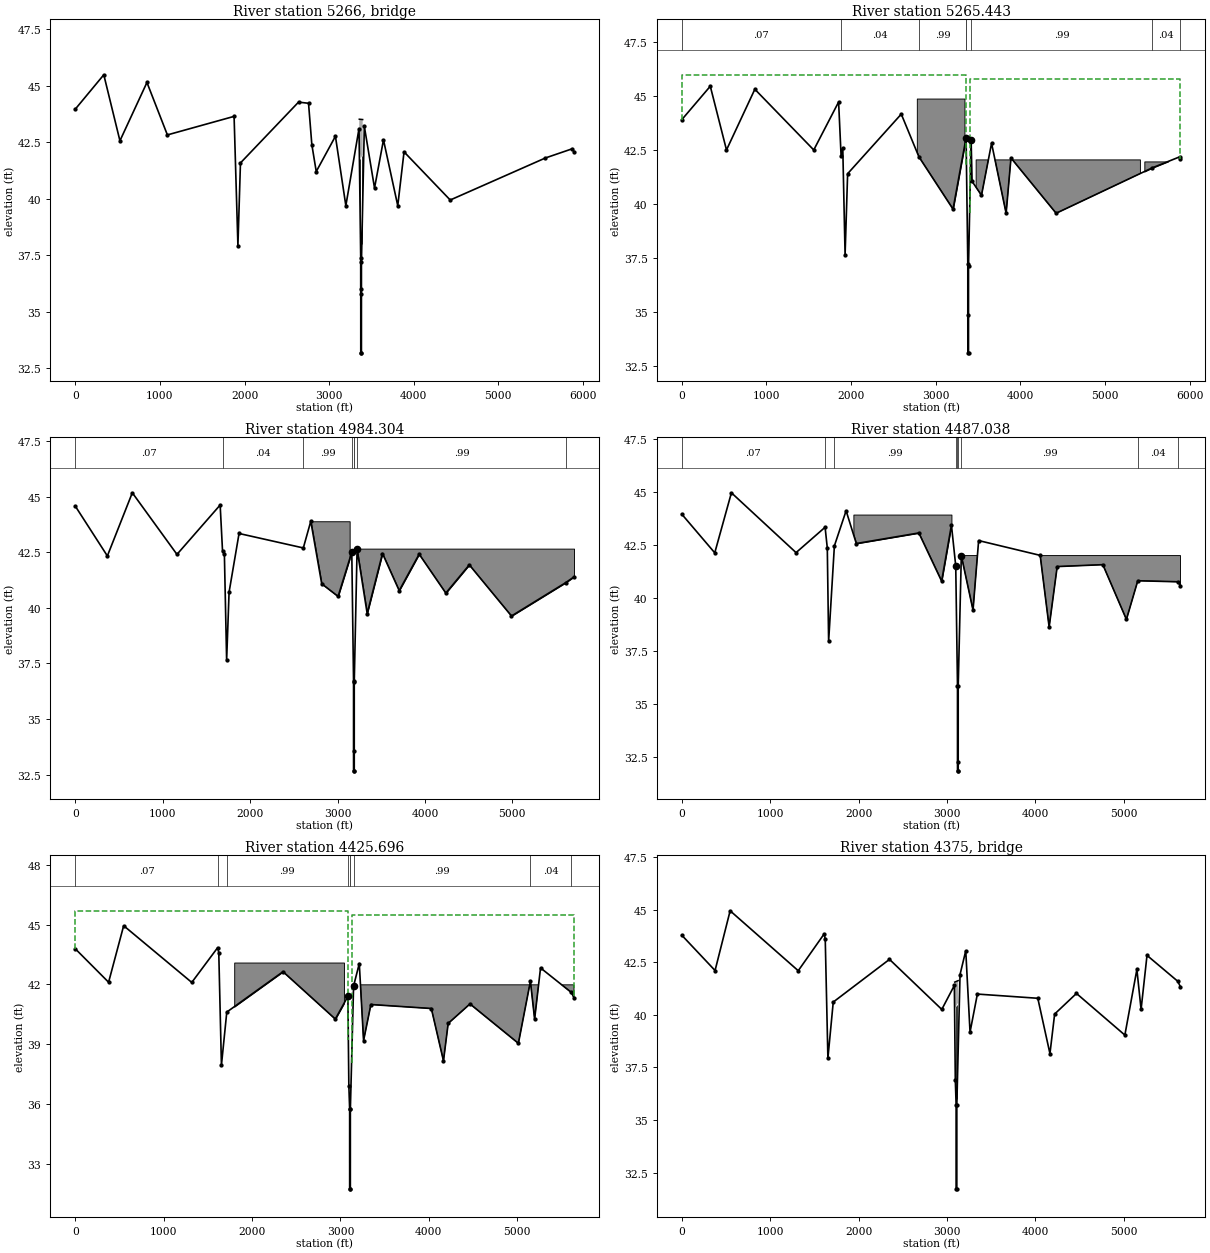
Type RM Length L Ch R = 3 ,5266    ,,,
BEGIN DESCRIPTION:
Wooden bridge
END DESCRIPTION:
Bridge Culvert--1,0,-1,-1, 0
Deck Dist Width WeirC Skew NumUp NumDn MinLoCord MaxHiCord MaxSubmerge Is_Ogee
0.5,23,2.6,0, 2, 2, , , 0.95, 0, 0,0,,
 3356.223396.297
  43.515    43.5
  41.718   41.92
 3362.68 3402.75
   43.66   43.55
   41.93   41.82
Pier Skew, UpSta & Num, DnSta & Num=  ,3365.87, 2 ,3372.47, 2 , 0 , 0 , 0 ,,
       1       1
  38.584   41.92
       1       1
  38.584   41.92
Pier Skew, UpSta & Num, DnSta & Num=  ,3386.253, 2 ,3392.853, 2 , 0 , 0 , 0 ,,
       1       1
 38.0645   41.92
       1       1
 38.0645   41.92
Abutment Skew #Up #Dn= , 6 , 6
  3353.83355.7763356.0253356.3573357.4323357.573
   42.89    43.5   45.86  41.733  41.838  41.104
 3360.363362.4343362.555  3362.83364.0653364.227
   42.87    43.6  46.025  41.934  41.975   40.91
Abutment Skew #Up #Dn= , 5 , 5
3394.6783394.8733396.121 3396.34 3411.76
  40.835  41.833  45.976    43.5   42.96
3401.1753401.4783402.5583402.625 3418.42
  40.873  41.906  45.882    43.5   42.91
BR Coef=-1 , 1 , 1 ,1.25, 0 ,,,0.8,-1,2,0,
WSPro=,,,, 1 ,,,, 0 ,,,, 0 ,,,,-1 ,-1 ,-1 , 0 , 0 , 0 , 0 , 0
BC Design=,, 0 ,, 0 ,,,,,,
BC HTab HWMax=45.48
BC Use User HTab Curves=0
BC User HTab FreeFlow(D)= 0

Type RM Length L Ch R = 1 ,5265.443,282.4,281.15,280.03
BEGIN DESCRIPTION:
Bridge Section 2 - DS Hickok St
END DESCRIPTION:
XS GIS Cut Line= 2
     3120109.716    13795205.527     3126000.499    13795358.829
#Sta/Elev= 30
       0   43.92  337.14   45.47  528.59   42.52  863.57   45.33 1559.68   42.52
 1853.31   44.74 1882.51   42.26 1902.59   42.62 1929.82   37.66 1959.83   41.42
  2593.8   44.18 2802.43    42.2 3205.25   39.78 3357.53   43.04 3359.75   43.06
 3379.87   37.26 3379.93   34.89 3380.41   33.13 3388.18   33.13  3388.3   37.14
 3418.93   42.99 3430.32   41.07 3541.52   40.42 3660.64   42.83 3832.63   39.59
 3890.02   42.15 4423.52   39.59 5557.83   41.69 5882.23    42.2 5892.78   42.12
#Mann= 8 ,-1 , 0
       0     .07       0 1882.51     .04       0 2802.43     .99       0
 3357.53     .04       0 3359.75    .015       0 3418.93     .99       0
 5557.83     .04       0 5882.23    .016       0
#XS Ineff= 2 , 0
       0  3364.1      46  3401.2       0    45.8
Permanent Ineff=
       F       F
#Block Obstruct= 3 ,-1
 2777.46 3340.29    44.9 3478.29 5419.45   42.06 5465.72 5848.87   41.99
Bank Sta=3359.75,3418.93
XS Rating Curve= 0 ,0
Exp/Cntr=0.5,0.3

Type RM Length L Ch R = 1 ,4984.304,467.91,497.26,496.54
BEGIN DESCRIPTION:
Bridge Section 1 - DS Hickok St
END DESCRIPTION:
XS GIS Cut Line= 2
     3120292.775    13795531.848     3125997.408    13795608.025
#Sta/Elev= 30
       0   44.57  366.96   42.33  652.28   45.17 1163.15    42.4 1657.26   44.62
 1684.39   42.55 1705.48   42.42 1731.26   37.64 1759.22    40.7 1873.27   43.34
 2608.56   42.69 2693.98   43.89 2818.92   41.08 3006.37   40.51 3162.96    42.5
 3183.06   36.72 3183.14   33.56 3183.39   32.67 3191.16   32.67 3191.29   36.67
 3223.55   42.63 3339.15   39.74  3514.3   42.44 3705.45   40.77 3933.57   42.41
 4238.79   40.66 4507.36   41.93 4989.86   39.63 5610.27   41.13 5705.14   41.39
#Mann= 8 ,-1 , 0
       0     .07       0 1684.39     .04       0 2608.56     .99       0
 3162.96     .04       0 3183.06    .015       0 3191.29     .04       0
 3223.55     .99       0 5610.27    .016       0
#Block Obstruct= 2 ,-1
 2693.98 3138.54   43.89 3228.75 5705.14   42.66
Bank Sta=3162.96,3223.55
XS Rating Curve= 0 ,0
Exp/Cntr=0.3,0.1

Type RM Length L Ch R = 1 ,4487.038,65.01,61.34,85.69
BEGIN DESCRIPTION:
Bridge Section 4 - US BOTANY RD
END DESCRIPTION:
XS GIS Cut Line= 4
     3120348.488    13795913.884     3123312.343     13796016.02
     3123425.475    13796071.097     3125975.726    13796076.595
#Sta/Elev= 30
       0   43.97  373.34   42.14  561.68   44.98 1293.07   42.15 1621.54   43.35
 1646.37   42.37 1661.38   37.95 1726.59   42.47 1859.17   44.13 1974.64   42.58
 2681.98   43.08 2939.57    40.8 3050.74   43.45 3099.37   41.52  3119.2   35.85
 3119.29   32.24  3119.4   31.83 3127.21   31.83 3127.35   35.84 3162.45   42.01
 3294.85   39.43 3358.34   42.72  4054.6   42.02 4155.92   38.63 4247.09   41.49
 4763.43   41.58 5030.25   38.99 5158.66   40.82 5616.65   40.77  5641.7   40.55
#Mann= 9 ,-1 , 0
       0     .07       0 1621.54     .04       0 1726.59     .99       0
 3099.37     .04       0  3119.2    .015       0 3127.35     .04       0
 3162.45     .99       0 5158.66     .04       0 5616.65    .016       0
#Block Obstruct= 2 ,-1
  1941.6 3050.74   43.95 3162.45  5641.7   42.01
Bank Sta=3099.37,3162.45
XS Rating Curve= 0 ,0
Exp/Cntr=0.5,0.3

Type RM Length L Ch R = 1 ,4425.696,43.96,50.34,49.64
BEGIN DESCRIPTION:
Bridge Section 3 - US BOTANY RD
END DESCRIPTION:
XS GIS Cut Line= 6
     3120356.447    13795985.515     3123312.722    13796087.796
     3123431.808    13796132.454     3123479.443    13796132.454
     3123650.629    13796200.928     3125975.726    13796214.168
#Sta/Elev= 30
       0   43.79  376.78   42.11  547.34   44.95 1317.83    42.1 1611.07   43.85
  1623.4   43.59 1653.42   37.94 1713.87   40.61 2350.24   42.64 2941.93   40.26
 3084.08    41.4 3094.82   36.92 3104.05   35.73 3104.15   31.73 3111.95   31.73
 3112.05   35.73 3148.43   41.92 3213.03   43.05  3261.5   39.18  3344.5   40.99
 4028.21   40.79  4165.5   38.16 4218.65   40.04 4465.51   41.02 5013.16   39.04
 5149.12   42.16 5196.68   40.26 5263.65   42.83 5611.11    41.6 5642.37   41.33
#Mann= 9 ,-1 , 0
       0     .07       0 1611.07     .04       0 1713.87     .99       0
 3084.08     .04       0 3104.05    .015       0 3112.05     .04       0
 3148.43     .99       0 5149.12     .04       0 5611.11    .016       0
#XS Ineff= 2 , 0
       0  3089.3    45.7  3125.7       0    45.5
Permanent Ineff=
       F       F
#Block Obstruct= 2 ,-1
 1797.93 3039.38    43.1 3226.56 5642.37   41.98
Bank Sta=3084.08,3148.43
XS Rating Curve= 0 ,0
Exp/Cntr=0.5,0.3

Type RM Length L Ch R = 3 ,4375    ,,,
BEGIN DESCRIPTION:
Botany St. Bridge
END DESCRIPTION:
Bridge Culvert--1,0,-1,-1, 0
Deck Dist Width WeirC Skew NumUp NumDn MinLoCord MaxHiCord MaxSubmerge Is_Ogee
0.15,49,2.6,0, 2, 2, , , 0.95, 0, 0,0,,
3088.219 3127.28
   41.56   41.63
   40.31   40.58
 3129.61 3168.29
  42.284   42.21
   40.93   40.81
Pier Skew, UpSta & Num, DnSta & Num=  ,3102.11, 2 ,3145.61, 2 , 0 , 0 , 0 ,,
       1       1
   36.28   40.58
       1       1
   36.28      41
Pier Skew, UpSta & Num, DnSta & Num=  ,3113.55, 2 ,3157.05, 2 , 0 , 0 , 0 ,,
       1       1
   36.28      41
       1       1
   36.28      41
Abutment Skew #Up #Dn= , 6 , 6
 3039.38 3087.83 3088.06 3088.43 3088.89  3089.3
   41.82    41.3   44.97   40.31    40.3   39.22
  3116.83129.1773129.274  3129.73130.3453130.399
   42.39  42.204   45.74  41.049  41.047  39.072
Abutment Skew #Up #Dn= , 6 , 6
 3125.67 3126.62 3127.18  3127.5 3127.71 3148.43
   39.15   40.55   40.55   45.01   41.77   41.92
3166.7723167.7453168.0963168.8733169.185 3173.13
   39.29    40.8    40.8  45.586  41.873   41.79
BR Coef=-1 , 1 , 1 ,1.25, 0 ,,,0.8,-1,2,0,
WSPro=,,,, 1 ,,,, 0 ,,,, 0 ,,,,-1 ,-1 ,-1 , 0 , 0 , 0 , 0 , 0
BC Design=,, 0 ,, 0 ,,,,,,
BC HTab HWMax=44.95
BC Use User HTab Curves=0
BC User HTab FreeFlow(D)= 0

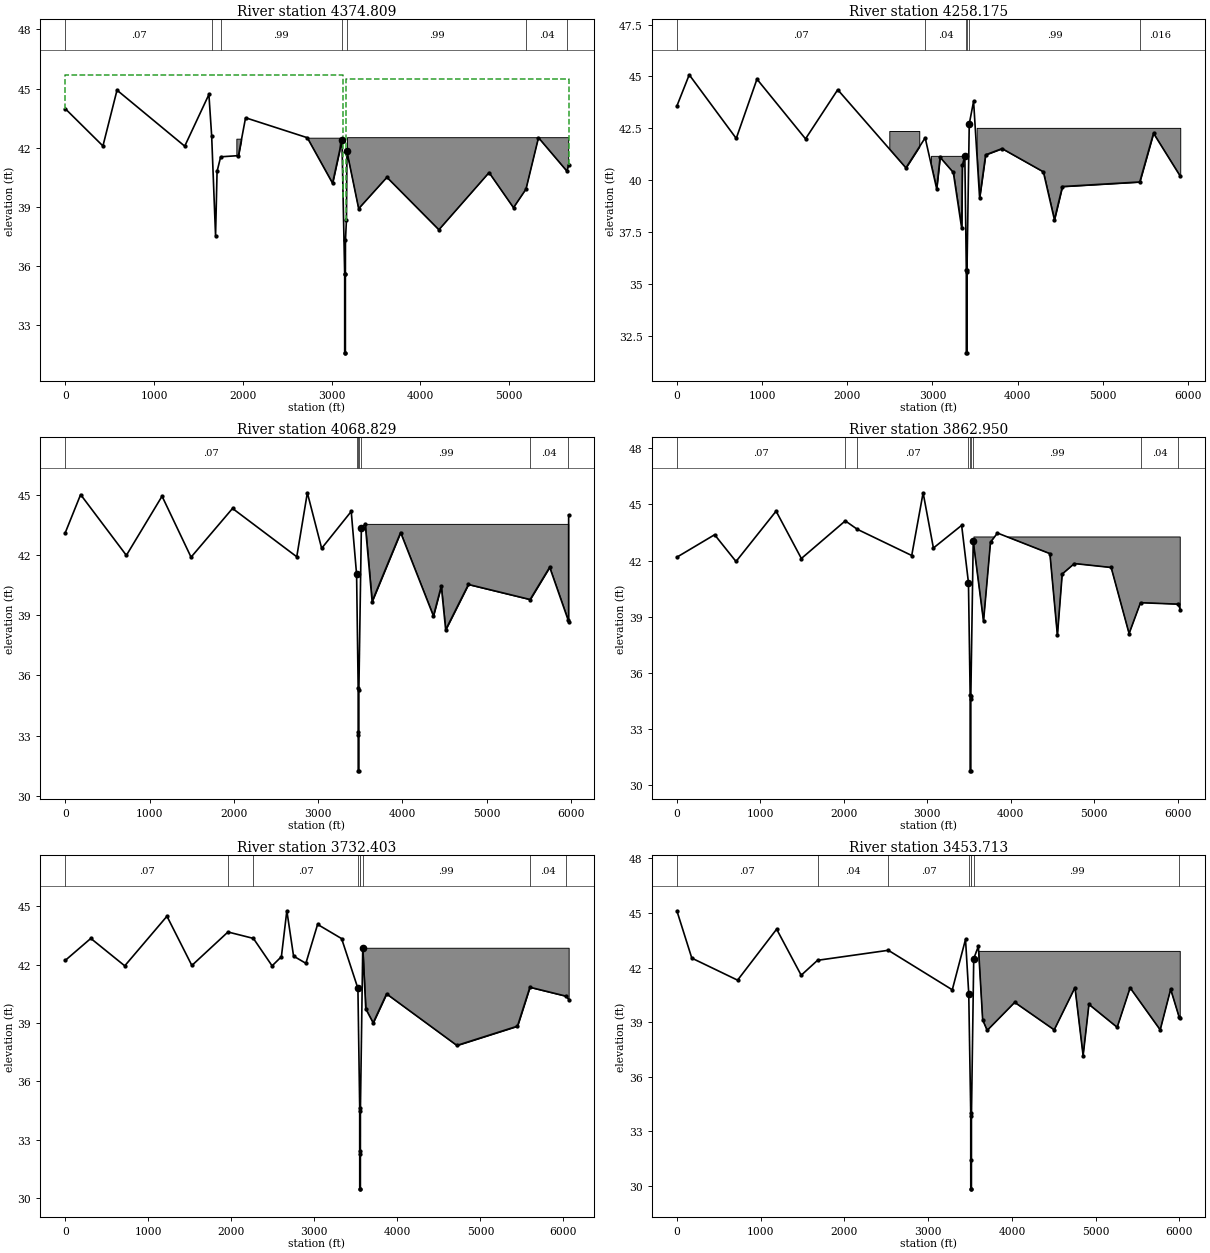
Type RM Length L Ch R = 1 ,4374.809,148.79,116.57,93.95
BEGIN DESCRIPTION:
Bridge Section 2 - DS BOTANY RD
END DESCRIPTION:
XS GIS Cut Line= 6
     3120316.652     13796033.27     3123313.832    13796127.663
     3123425.475    13796182.741     3123476.087    13796182.741
      3123650.25    13796249.727      3125960.44    13796280.407
#Sta/Elev= 30
       0   43.98  424.19   42.09  582.87   44.92 1345.66   42.08 1618.03    44.7
 1649.17    42.6 1693.07   37.53 1710.01    40.8 1750.62   41.54  1950.9    41.6
 2031.06   43.52 2725.99   42.51 3010.88    40.2  3116.8   42.39 3147.55    35.6
 3147.65    31.6 3155.45    31.6 3155.55    35.6  3156.4    37.3 3167.52   38.35
 3173.15   41.81 3305.33   38.91 3623.86    40.5 4209.07   37.84 4774.49   40.74
 5049.55   38.96 5190.17    39.9 5330.96   42.51 5651.82   40.81 5670.76   41.13
#Mann= 7 ,-1 , 0
       0     .07       0 1649.17     .04       0 1750.62     .99       0
  3116.8    .015       0 3173.15     .99       0 5190.17     .04       0
 5651.82    .016       0
#XS Ineff= 2 , 0
       0  3130.4    45.7  3166.8       0    45.5
Permanent Ineff=
       F       F
#Block Obstruct= 4 ,-1
 2725.99 3090.93   42.51 3179.31 5670.76   42.51 1927.31 1982.11   42.46
 2481.17 2725.99   42.51
Bank Sta=3116.8,3173.15
XS Rating Curve= 0 ,0
Exp/Cntr=0.5,0.3

Type RM Length L Ch R = 1 ,4258.175,189.84,189.32,188.95
BEGIN DESCRIPTION:
Bridge Section 1 - DS Botany
END DESCRIPTION:
XS GIS Cut Line= 2
     3120046.044    13796256.124     3125953.396    13796330.917
#Sta/Elev= 30
       0   43.57  145.12   45.08  696.85   42.01  940.09   44.87 1510.04   41.99
 1887.99   44.36 2688.32   40.59 2914.21   42.04 3049.19   39.58  3089.5    41.1
 3244.29   40.37  3343.1   37.67 3350.37   40.71  3379.6   41.17 3396.97   35.68
  3397.1   31.67  3404.9   31.67    3405   35.59    3405   35.67 3431.56   42.71
  3482.4    43.8 3553.12   39.14 3623.94   41.22 3816.76   41.52 4301.31    40.4
 4431.11   38.09 4524.68   39.69 5432.78   39.91 5593.98   42.26 5907.83   40.19
#Mann= 6 ,-1 , 0
       0     .07       0 2914.21     .04       0 3396.97    .015       0
    3405     .04       0 3431.56     .99       0 5432.78    .016       0
#Block Obstruct= 3 ,-1
 2493.22 2844.91   42.37 2983.03  3379.6   41.17 3518.68 5907.83   42.52
Bank Sta=3379.6,3431.56
XS Rating Curve= 0 ,0
Exp/Cntr=0.3,0.1

Type RM Length L Ch R = 1 ,4068.829,206.33,205.82,206.39
XS GIS Cut Line= 2
     3119958.494    13796463.059     3125930.509    13796506.387
#Sta/Elev= 30
       0   43.11  182.11   45.01  724.84   41.98 1148.14   44.93 1492.34   41.89
  1984.4   44.32 2746.36   41.91 2872.01    45.1 3041.69   42.33 3392.55   44.17
 3456.27   41.03  3474.9   35.36 3474.96   33.17 3475.31   33.05 3475.35   31.24
 3483.15   31.24 3483.27   35.25 3512.75   43.32 3558.45   43.55 3640.48   39.68
 3978.57   43.12  4367.9   38.96 4461.09   40.45 4513.04   38.27 4783.09   40.53
 5515.06   39.78 5747.09   41.39 5967.46   38.74    5972   38.68 5972.17      44
#Mann= 7 ,-1 , 0
       0     .07       0 3456.27     .04       0  3474.9    .015       0
 3483.27     .04       0 3512.75     .99       0 5515.06     .04       0
 5967.46    .016       0
#Block Obstruct= 1 ,-1
 3558.45 5967.46   43.55
Bank Sta=3456.27,3512.75
XS Rating Curve= 0 ,0
Exp/Cntr=0.3,0.1

Type RM Length L Ch R = 1 ,3862.950,129.83,130.56,133.75
XS GIS Cut Line= 2
     3119910.739    13796685.913     3125940.045    13796699.658
#Sta/Elev= 30
       0   42.18  452.27   43.38  708.42   41.95 1188.63   44.64 1491.28   42.11
 2017.17   44.12 2161.45   43.67 2813.08   42.27 2949.52   45.62 3072.71   42.67
 3411.03   43.88  3492.6   40.82 3512.95    34.8  3513.1   30.77  3520.9   30.77
 3521.02    34.6 3521.02   34.77 3549.78   43.04 3673.15   38.76 3756.74   42.98
 3840.04   43.47 4468.15   42.37 4558.15      38 4615.67   41.28  4761.4   41.84
  5201.9   41.63 5416.71    38.1 5553.43   39.75 6006.35   39.67 6029.32   39.38
#Mann= 9 ,-1 , 0
       0     .07       0 2017.17     .04       0 2161.45     .07       0
  3492.6     .04       0 3512.95    .015       0 3521.02     .04       0
 3549.78     .99       0 5553.43     .04       0 6006.35    .016       0
#Block Obstruct= 1 ,-1
 3558.42 6029.32   43.26
Bank Sta=3492.6,3549.78
XS Rating Curve= 0 ,0
Exp/Cntr=0.3,0.1

Type RM Length L Ch R = 1 ,3732.403,279.2,278.65,283.2
XS GIS Cut Line= 2
     3119870.944    13796789.381     3125933.688    13796849.062
#Sta/Elev= 30
       0   42.22  307.79   43.35  716.38   41.94 1224.72   44.49 1524.63   41.96
 1959.76   43.68 2265.88   43.35 2491.11   41.94 2603.06   42.41 2668.71   44.77
 2749.76   42.44 2897.99   42.07  3039.1   44.07 3328.47   43.34 3524.79   40.78
 3546.25   34.63 3546.31   32.43 3546.72   32.29 3546.77   30.48 3554.56   30.48
 3554.68   34.48 3582.97   42.87 3619.23   39.73 3708.33   39.01 3869.89    40.5
 4716.66   37.85 5446.48   38.84 5596.18   40.84 6033.93   40.38 6063.04   40.21
#Mann= 9 ,-1 , 0
       0     .07       0 1959.76     .04       0 2265.88     .07       0
 3524.79     .04       0 3546.25    .015       0 3554.68     .04       0
 3582.97     .99       0 5596.18     .04       0 6033.93    .016       0
#Block Obstruct= 1 ,-1
 3582.97 6063.04   42.87
Bank Sta=3524.79,3582.97
XS Rating Curve= 0 ,0
Exp/Cntr=0.3,0.1

Type RM Length L Ch R = 1 ,3453.713,640.99,641.15,641.33
XS GIS Cut Line= 2
     3119894.821    13797083.867     3125905.079    13797116.081
#Sta/Elev= 30
       0   45.12  178.46   42.52  724.93   41.31 1191.17   44.11 1484.43   41.58
 1679.83    42.4 2524.77   42.95 3288.49   40.78 3446.52   43.55 3484.97   40.57
 3508.85   33.99 3508.94   31.44 3509.35   29.85 3517.14   29.85 3517.25   33.85
 3544.57   42.49 3600.15   43.17  3651.2   39.13  3705.5   38.55 4034.12   40.09
 4505.56   38.58 4753.49    40.9 4850.81   37.16 4920.22   39.98 5257.46   38.72
 5411.81   40.89 5771.15   38.58 5896.08   40.81 5996.58   39.29 6010.34   39.21
#Mann= 8 ,-1 , 0
       0     .07       0 1679.83     .04       0 2524.77     .07       0
 3484.97     .04       0 3508.85    .015       0 3517.25     .04       0
 3544.57     .99       0 5996.58    .016       0
#Block Obstruct= 1 ,-1
 3575.43 6010.34   42.89
Bank Sta=3484.97,3544.57
XS Rating Curve= 0 ,0
Exp/Cntr=0.3,0.1