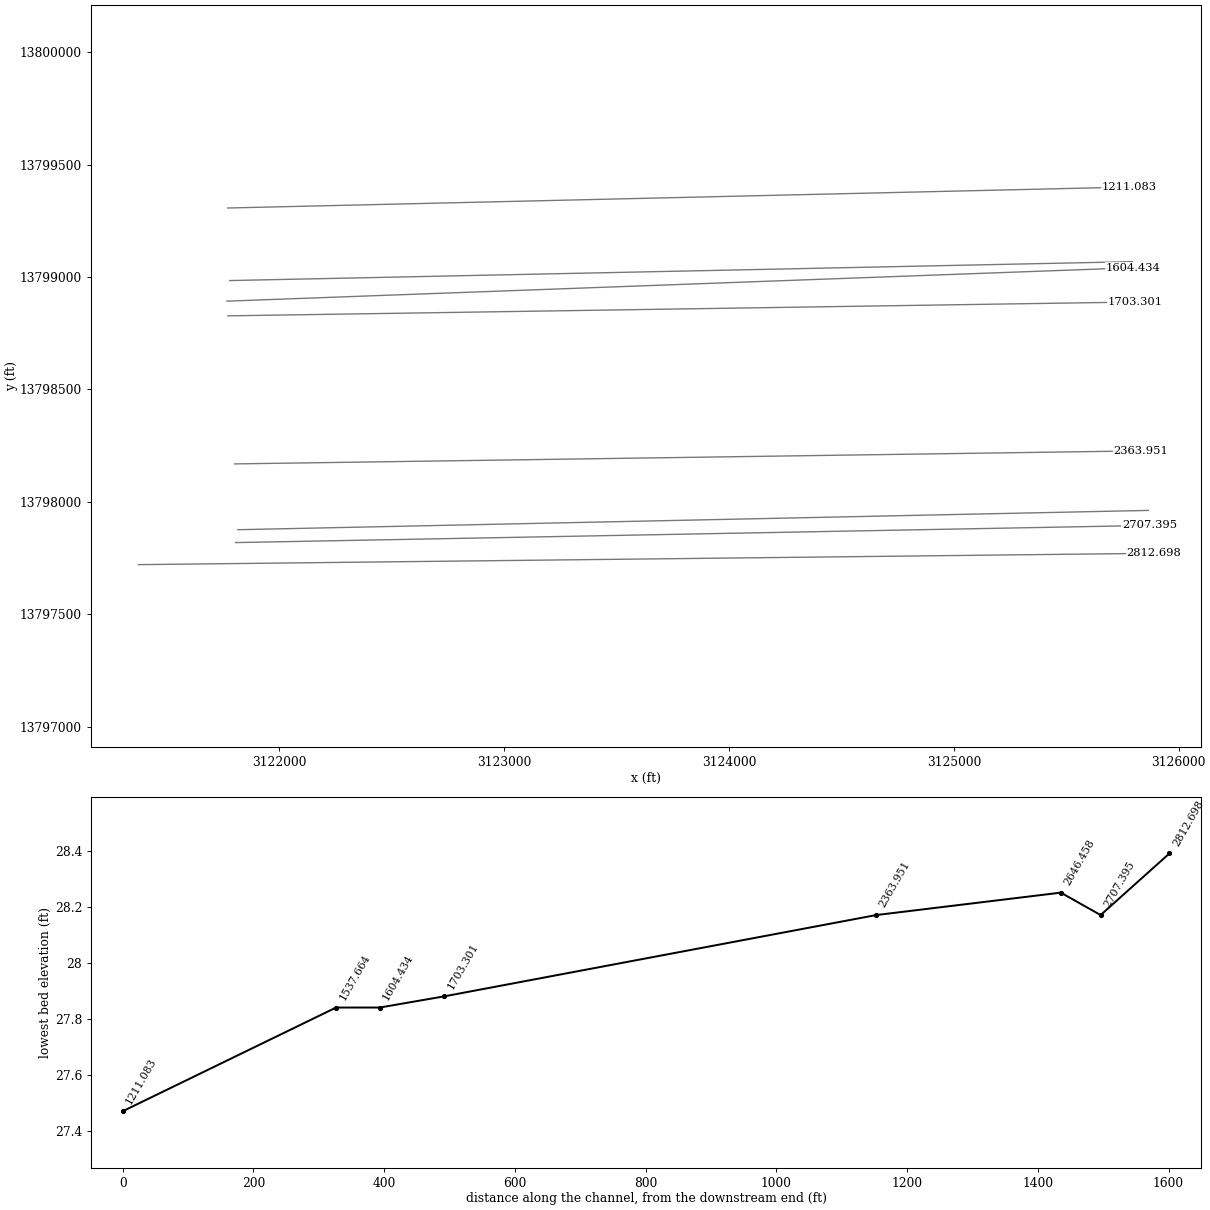
HEC-RAS study C127-00-00.prj: C127-00-00

--- C127-00-00.g01 (geometry) --- (continued)

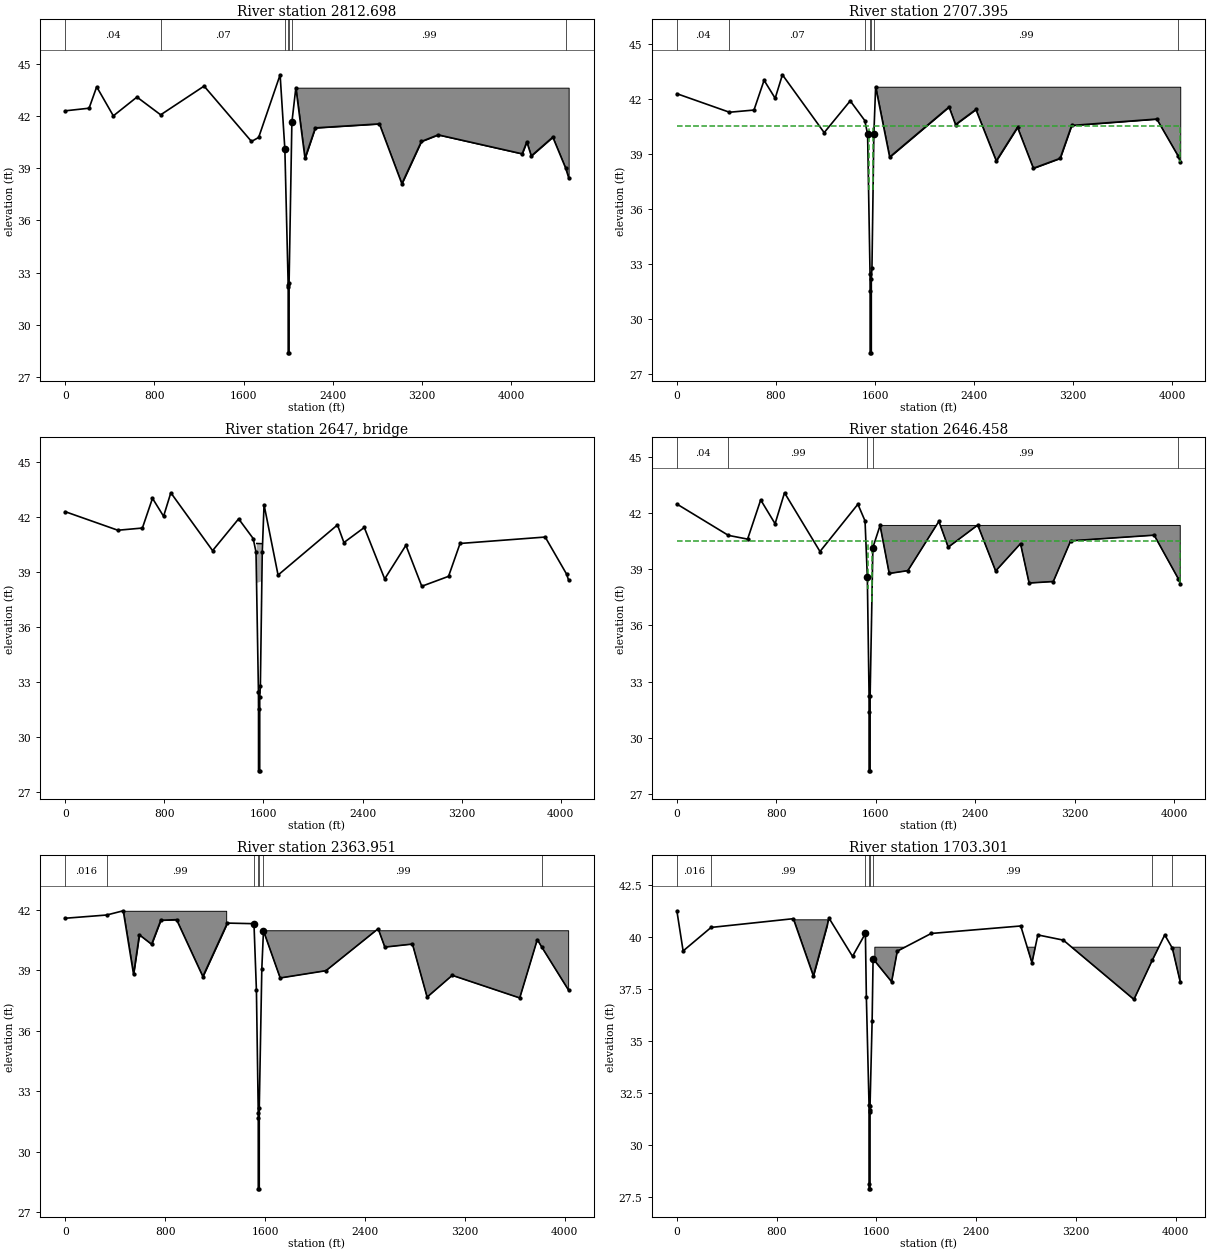
Type RM Length L Ch R = 1 ,2812.698,104.53,105.32,105.93
BEGIN DESCRIPTION:
Bridge Section 4 - Hartsville St. US
END DESCRIPTION:
XS GIS Cut Line= 2
     3121373.616    13797720.592     3125888.895    13797771.009
#Sta/Elev= 30
       0   42.29  213.63   42.44  281.81   43.67  431.05      42  643.07   43.08
  855.65   42.06 1245.19   43.71 1670.46   40.53 1734.66   40.76 1927.29   44.36
 1969.85   40.08 1999.57   32.26 1999.65   32.17 1999.74   28.39 2007.52   28.39
 2007.62   32.39 2032.66   41.62 2068.52   43.62  2150.4   39.56 2242.74   41.31
 2817.86   41.54 3019.29    38.1  3194.4   40.53 3345.08   40.91 4098.69   39.82
 4140.11   40.51 4180.33    39.7 4373.26   40.78 4488.69      39 4515.56   38.45
#Mann= 7 ,-1 , 0
       0     .04       0  855.65     .07       0 1969.85     .04       0
 1999.57    .015       0 2007.62     .04       0 2032.66     .99       0
 4488.69    .016       0
#Block Obstruct= 1 ,-1
 2068.52 4515.56   43.62
Bank Sta=1969.85,2032.66
XS Rating Curve= 0 ,0
Exp/Cntr=0.5,0.3

Type RM Length L Ch R = 1 ,2707.395,60.61,60.86,61.05
BEGIN DESCRIPTION:
Bridge Section 3 - Hartsville St. US
END DESCRIPTION:
XS GIS Cut Line= 2
     3121805.992    13797818.706     3125869.816    13797895.022
#Sta/Elev= 30
       0   42.28   424.7   41.27  622.65   41.39  704.18   43.01  793.77   42.03
  852.26   43.31  1189.5   40.16 1399.84   41.89 1517.17   40.82 1540.11   40.08
 1559.76   32.47 1560.48   31.53 1560.59   28.17 1570.01   28.17 1570.12   32.17
 1575.27   32.79 1590.55   40.07 1604.97   42.66 1718.19   38.83 2197.81   41.56
 2249.91    40.6 2414.38   41.42 2579.12   38.62 2750.45   40.45  2878.6   38.22
 3094.69   38.76 3187.67   40.55 3875.13    40.9    4048   38.88 4064.54   38.54
#Mann= 7 ,-1 , 0
       0     .04       0   424.7     .07       0 1517.17     .04       0
 1559.76    .015       0 1570.12     .04       0 1590.55     .99       0
    4048    .016       0
#XS Ineff= 2 , 0
       0    1548    40.5  1584.2       0    40.5
Permanent Ineff=
       F       F
#Block Obstruct= 1 ,-1
 1604.97 4064.54   42.66
Bank Sta=1540.11,1590.55
XS Rating Curve= 0 ,0
Exp/Cntr=0.5,0.3

Type RM Length L Ch R = 3 ,2647    ,,,
BEGIN DESCRIPTION:
Hartsville Bridge
END DESCRIPTION:
Bridge Culvert--1,0,-1,-1, 0
Deck Dist Width WeirC Skew NumUp NumDn MinLoCord MaxHiCord MaxSubmerge Is_Ogee
0.5,60,2.6,0, 2, 2, , , 0.95, 0, 0,0,,
1546.2461586.366
   40.55   40.54
    38.4   38.49
1532.2271570.973
   40.49   40.56
   38.39   38.45
Abutment Skew #Up #Dn= , 7 , 8
    1540 1540.981541.293 1546.181546.4541548.0441548.152
      40   40.55   40.55   40.55   40.55  38.354  37.996
    15201526.116 1526.221531.9851531.9871532.3821533.9181534.005
      40    40.5    40.5    40.5    40.5    40.5  38.374   37.93
Abutment Skew #Up #Dn= , 8 , 7
1584.2271584.3921585.9091586.2791586.286 1590.781590.948    1593
  38.085  38.432   40.55   40.55   40.55   40.55   40.55      40
1569.0951569.1481570.5951570.9431575.1781575.279    1578
  38.014  38.413   40.55   40.55   40.55   40.55      39
BR Coef=-1 , 0 , 0 ,, 0 ,,,0.8,-1,,1,
WSPro=,,,, 1 ,,,, 0 ,,,, 0 ,,,,-1 ,-1 ,-1 , 0 , 0 , 0 , 0 , 0
BC Design=,, 0 ,, 0 ,,,,,,
BC HTab HWMax=43.31
BC Use User HTab Curves=0
BC User HTab FreeFlow(D)= 0

Type RM Length L Ch R = 1 ,2646.458,283.4,282.5,282.12
BEGIN DESCRIPTION:
Bridge Section 2 - Hartsville St. DS
END DESCRIPTION:
XS GIS Cut Line= 2
     3121815.532    13797875.943     3125865.047    13797961.798
#Sta/Elev= 30
       0   42.47   414.6    40.8  569.23    40.6  674.48   42.69  790.38   41.42
  866.17   43.07 1151.64   39.94 1456.63   42.46 1514.14   41.57 1532.54   38.59
 1546.55   32.26 1546.64   31.38 1546.72   28.25 1554.93   28.25 1555.07   32.26
 1577.21   40.15 1635.16   41.33 1708.73   38.77 1858.76   38.92 2108.39   41.55
 2183.42   40.17 2421.13   41.35 2565.19    38.9 2765.08   40.36 2834.34   38.26
 3029.03   38.34 3169.05   40.51 3840.67   40.81 4033.82    38.5 4050.43   38.22
#Mann= 5 ,-1 , 0
       0     .04       0   414.6     .99       0 1532.54    .015       0
 1577.21     .99       0 4033.82    .016       0
#XS Ineff= 2 , 0
       0    1534    40.5  1569.1       0    40.5
Permanent Ineff=
       F       F
#Block Obstruct= 1 ,-1
 1635.16 4050.43   41.33
Bank Sta=1532.54,1577.21
XS Rating Curve= 0 ,0
Exp/Cntr=0.5,0.3

Type RM Length L Ch R = 1 ,2363.951,660.36,660.64,660.55
BEGIN DESCRIPTION:
Bridge Section 1 - Hartsville St. DS
END DESCRIPTION:
XS GIS Cut Line= 2
     3121801.504    13798168.601     3125832.506    13798226.635
#Sta/Elev= 30
       0   41.58  331.54   41.74  464.23   41.95  546.86    38.8  593.36   40.76
  691.47   40.29  764.77   41.48  891.31   41.51 1101.79   38.69 1297.77   41.34
 1511.26   41.31 1530.87      38 1545.58   31.91 1545.61    31.7 1545.69   28.17
 1553.47   28.17 1553.58   32.17 1574.07   39.08 1587.27   40.96 1721.23   38.62
 2087.76   38.98 2505.84   41.06 2559.26   40.15 2780.42    40.3 2897.94   37.67
 3099.11   38.75 3639.71   37.63 3780.28   40.52 3817.27   40.14 4031.42   38.01
#Mann= 7 ,-1 , 0
       0    .016       0  331.54     .99       0 1511.26     .04       0
 1545.58    .015       0 1553.58     .04       0 1587.27     .99       0
 3817.27     .04       0
#Block Obstruct= 2 ,-1
  464.23 1288.68   41.95 1587.26 4031.42   40.96
Bank Sta=1511.26,1587.27
XS Rating Curve= 0 ,0
Exp/Cntr=0.3,0.1

Type RM Length L Ch R = 1 ,1703.301,96.6,98.89,100.56
BEGIN DESCRIPTION:
Bridge Section 4 - South Acres US
END DESCRIPTION:
XS GIS Cut Line= 3
      3121770.98    13798827.053     3123810.711    13798858.183
     3125807.997     13798888.65
#Sta/Elev= 30
       0   41.24    50.2   39.31  274.51   40.44  934.19   40.86 1094.77   38.11
 1220.93   40.88 1408.92   39.05 1512.16   40.15 1519.87    37.1  1541.4   31.89
 1541.49   28.09 1541.54   27.88 1549.34   27.88 1549.44   31.57 1549.47   31.69
 1549.47   31.88  1566.2   35.96 1573.85   38.93 1722.55   37.83 1768.11    39.3
 2039.97   40.15 2758.22   40.51 2848.22   38.74 2895.26   40.08 3099.58   39.83
 3666.11   36.98 3813.81   38.87 3913.36   40.08 3974.26   39.44 4037.49   37.82
#Mann= 8 ,-1 , 0
       0    .016       0  274.51     .99       0 1512.16     .04       0
  1541.4    .015       0 1549.47     .04       0 1573.85     .99       0
 3813.81     .04       0 3974.26    .016       0
#Block Obstruct= 2 ,-1
  923.96 1206.19   40.83 1587.91 4037.49   39.49
Bank Sta=1512.16,1573.85
XS Rating Curve= 0 ,0
Exp/Cntr=0.5,0.3

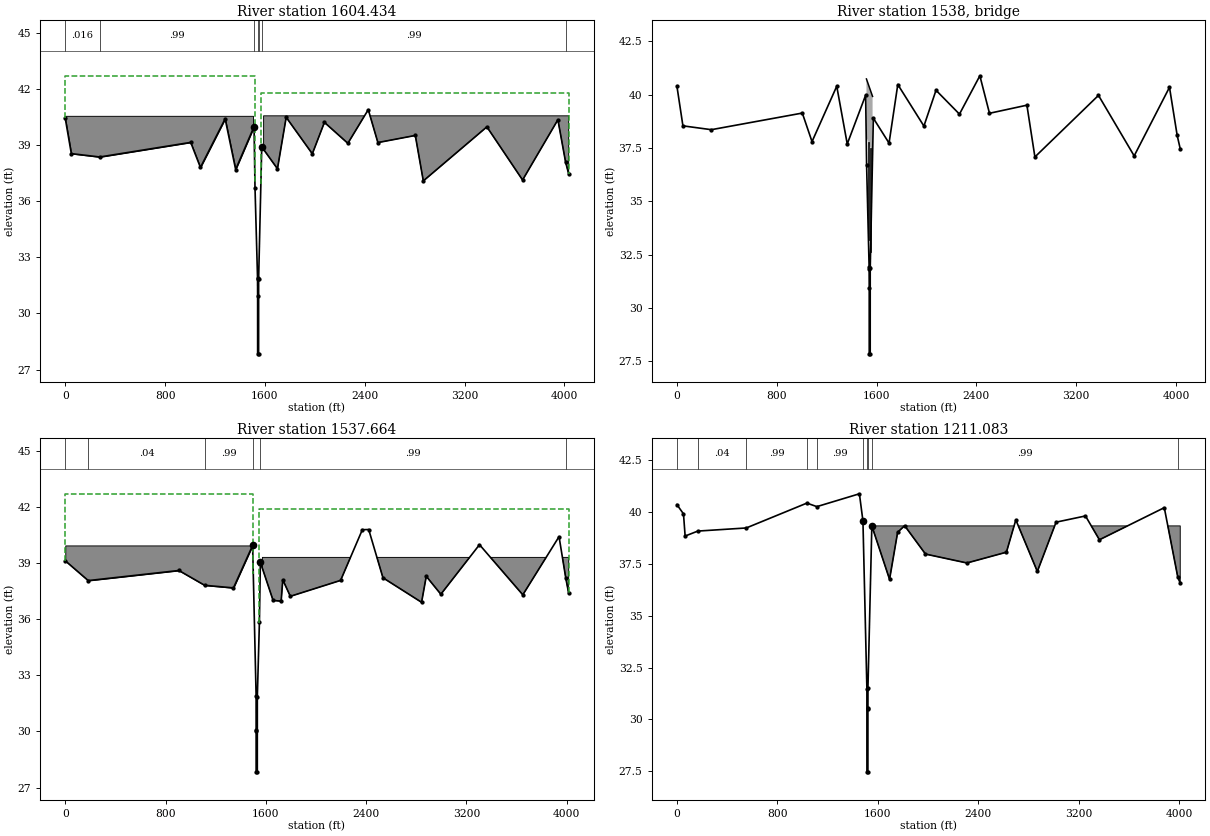
Type RM Length L Ch R = 1 ,1604.434,68.48,66.74,65.44
BEGIN DESCRIPTION:
Bridge Section 3 - South Acres US
END DESCRIPTION:
XS GIS Cut Line= 2
     3121766.619    13798892.462     3125797.841    13799040.986
#Sta/Elev= 30
       0   40.42   48.55   38.54  276.49   38.36 1005.25   39.14 1083.13    37.8
 1281.27    40.4 1365.38   37.69 1512.84   39.98 1520.49   36.71  1540.7   31.91
  1540.7   31.84 1541.51   30.92 1541.58   27.84 1549.38   27.84 1549.51   31.85
 1574.51    38.9 1700.42   37.73 1770.41   40.48 1979.77   38.53 2076.78   40.21
 2264.63   39.09 2428.13   40.89 2505.17   39.13 2805.15   39.51 2869.21   37.08
 3378.68   39.97 3664.75   37.13 3947.74   40.35 4009.39   38.09 4033.96   37.46
#Mann= 7 ,-1 , 0
       0    .016       0  276.49     .99       0 1512.84     .04       0
  1540.7    .015       0 1549.51     .04       0 1574.51     .99       0
 4009.39    .016       0
#XS Ineff= 2 , 0
       0    1520    42.7  1567.5       0    41.8
Permanent Ineff=
       F       F
#Block Obstruct= 2 ,-1
       0 1504.13   40.56 1589.38 4033.96   40.56
Bank Sta=1512.84,1574.51
XS Rating Curve= 0 ,0
Exp/Cntr=0.5,0.3

Type RM Length L Ch R = 3 ,1538    ,,,
BEGIN DESCRIPTION:
South Acres Bridge
END DESCRIPTION:
Bridge Culvert--1,0,-1,-1, 0
Deck Dist Width WeirC Skew NumUp NumDn MinLoCord MaxHiCord MaxSubmerge Is_Ogee
0.3,65,2.6,0, 2, 2, , , 0.95, 0, 0,0,,
1519.2521568.222
 40.7405 39.9226
 38.0121 37.2491
1499.8671549.559
 40.7619 40.0166
 37.9645  37.371
Pier Skew, UpSta & Num, DnSta & Num=  ,1535.306, 2 ,1516.936, 2 , 0 , 0 , 0 ,,
     1.3     1.3
  32.722 38.0121
     1.3     1.3
  32.722 38.0121
Pier Skew, UpSta & Num, DnSta & Num=  ,1552.289, 2 ,1534.799, 2 , 0 , 0 , 0 ,,
     1.3     1.3
 32.4118 38.0121
     1.3     1.3
 32.4118 38.0121
Abutment Skew #Up #Dn= , 8 , 7
1512.6881513.5341514.8021515.783 1519.091519.4581520.0061520.115
  39.952  41.523  41.561  42.576  42.746  38.027  38.074  36.635
1493.2571494.3011495.5631496.841 1499.851499.9041500.762
  39.869  41.518  41.509  42.602  42.764  37.984  37.947
Abutment Skew #Up #Dn= , 8 , 8
1567.533 1567.55  1568.21568.2311571.6121572.6651573.995 1574.96
  35.941  37.258  37.244  41.887  41.667  40.618   40.59  38.894
1548.6271548.857  1549.5 1549.571552.9991554.0781555.4861556.364
  36.232  37.352  37.354  42.033  41.854  40.777  40.728  39.319
BR Coef=-1 , 1 , 1 ,1.05, 0 ,,,0.8,-1,1.2,0,
WSPro=,,,, 1 ,,,, 0 ,,,, 0 ,,,,-1 ,-1 ,-1 , 0 , 0 , 0 , 0 , 0
BC Design=,, 0 ,, 0 ,,,,,,
BC HTab HWMax=40.89
BC Use User HTab Curves=0
BC User HTab FreeFlow(D)= 0

Type RM Length L Ch R = 1 ,1537.664,326.41,326.42,326.54
BEGIN DESCRIPTION:
Bridge Section 2 - South Acres DS
END DESCRIPTION:
XS GIS Cut Line= 2
     3121779.701    13798984.034     3125794.456    13799068.068
#Sta/Elev= 30
       0   39.12  183.15   38.06  906.69    38.6 1111.69   37.81 1341.75   37.67
 1494.59   39.94 1522.33   31.91 1522.38   30.09 1522.51   30.02 1522.52   27.84
  1531.9   27.84 1532.02   31.84  1548.7   35.84 1556.29   39.04 1657.94      37
 1722.22   36.96 1735.13    38.1 1795.46   37.22  2196.4   38.07 2369.82   40.78
 2420.54   40.79 2534.33   38.21 2842.38    36.9  2879.8   38.29 2996.06   37.33
 3304.35   39.98 3649.98    37.3 3938.98   40.41 3992.83   38.19 4015.63   37.39
#Mann= 6 ,-1 , 0
       0    .016       0  183.15     .04       0 1111.69     .99       0
 1494.59    .015       0 1556.29     .99       0 3992.83    .016       0
#XS Ineff= 2 , 0
       0  1499.9    42.7  1548.6       0    41.9
Permanent Ineff=
       F       F
#Block Obstruct= 2 ,-1
       0 1494.59   39.94 1572.62 4015.63    39.3
Bank Sta=1494.59,1556.29
XS Rating Curve= 0 ,0
Exp/Cntr=0.5,0.3

Type RM Length L Ch R = 1 ,1211.083,759.36,755.25,754.12
BEGIN DESCRIPTION:
Bridge Section 1 - South Acres DS
END DESCRIPTION:
XS GIS Cut Line= 2
      3121770.98    13799306.719     3125777.529     13799399.82
#Sta/Elev= 30
       0   40.37   52.71   39.92   65.82   38.85  166.88   39.09  552.41   39.24
 1035.17   40.44 1114.56   40.27 1453.29   40.89 1481.39   39.58 1512.95   31.47
 1513.08   27.47 1520.92   27.47 1521.02    30.5  1521.2   30.55 1521.29   31.54
 1552.29   39.34 1693.36   36.76 1757.63   39.03 1813.39   39.35  1979.4   37.98
 2309.29   37.55 2623.72   38.07 2698.63   39.63 2869.92   37.14 3019.16   39.52
 3253.13   39.82 3364.11   38.67 3880.59   40.22 3987.31   36.89 4007.63   36.57
#Mann= 10 ,-1 , 0
       0    .016       0  166.88     .04       0  552.41     .99       0
 1035.17     .04       0 1114.56     .99       0 1481.39     .04       0
 1512.95    .015       0 1521.29     .04       0 1552.29     .99       0
 3987.31    .016       0
#Block Obstruct= 1 ,-1
 1552.29 4007.63   39.34
Bank Sta=1481.39,1552.29
XS Rating Curve= 0 ,0
Exp/Cntr=0.3,0.1