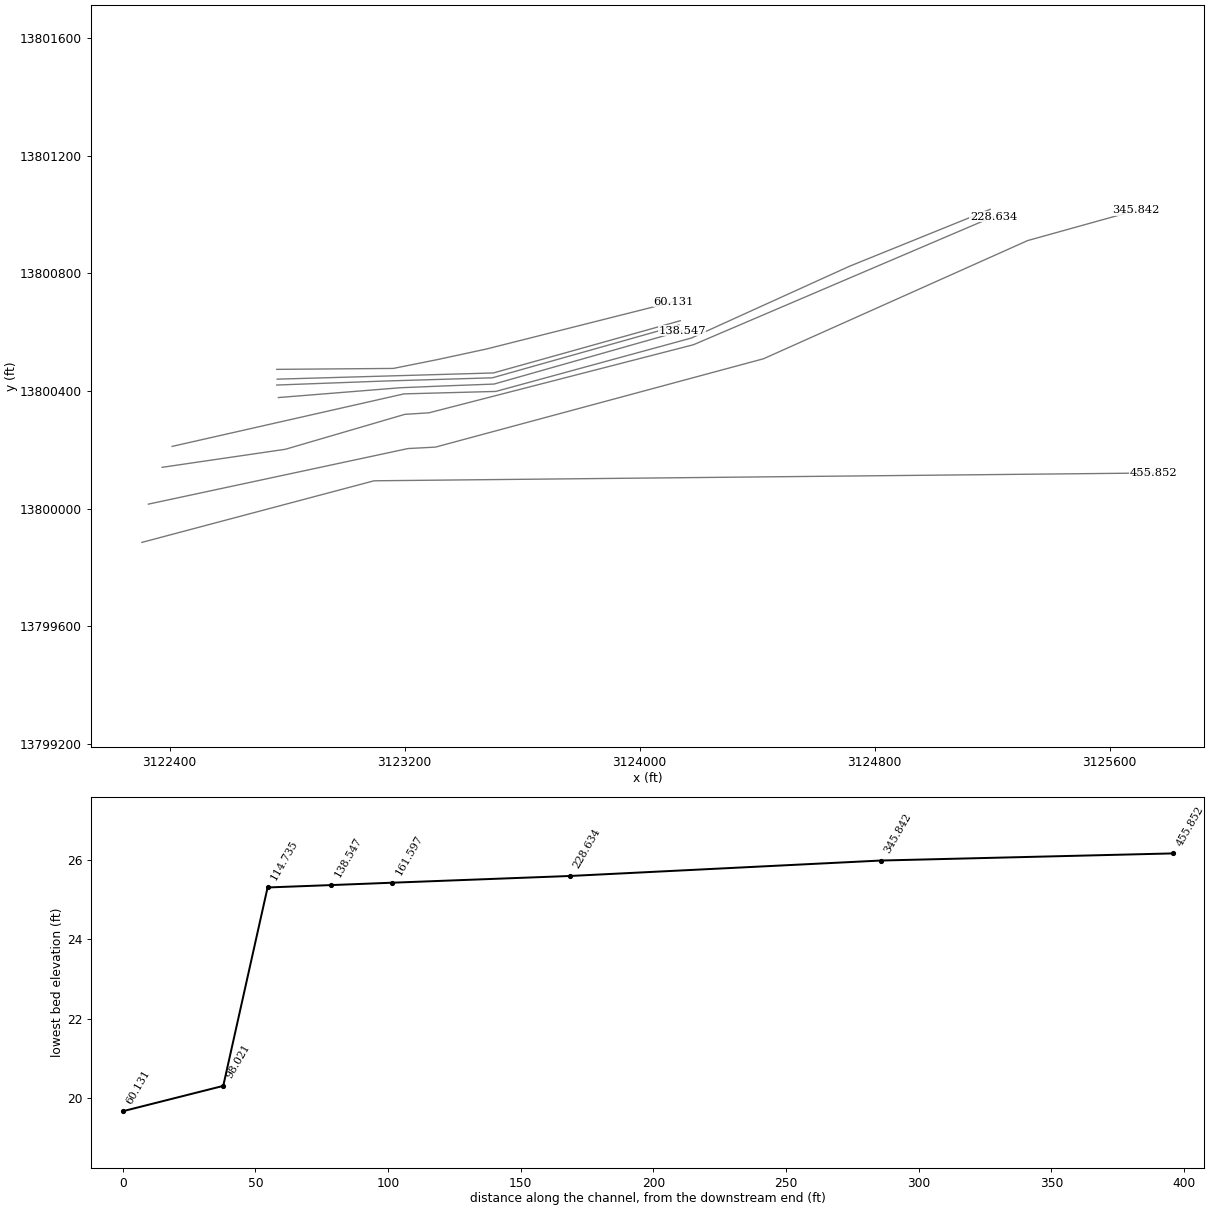
HEC-RAS study C127-00-00.prj: C127-00-00

--- C127-00-00.g01 (geometry) --- (continued)

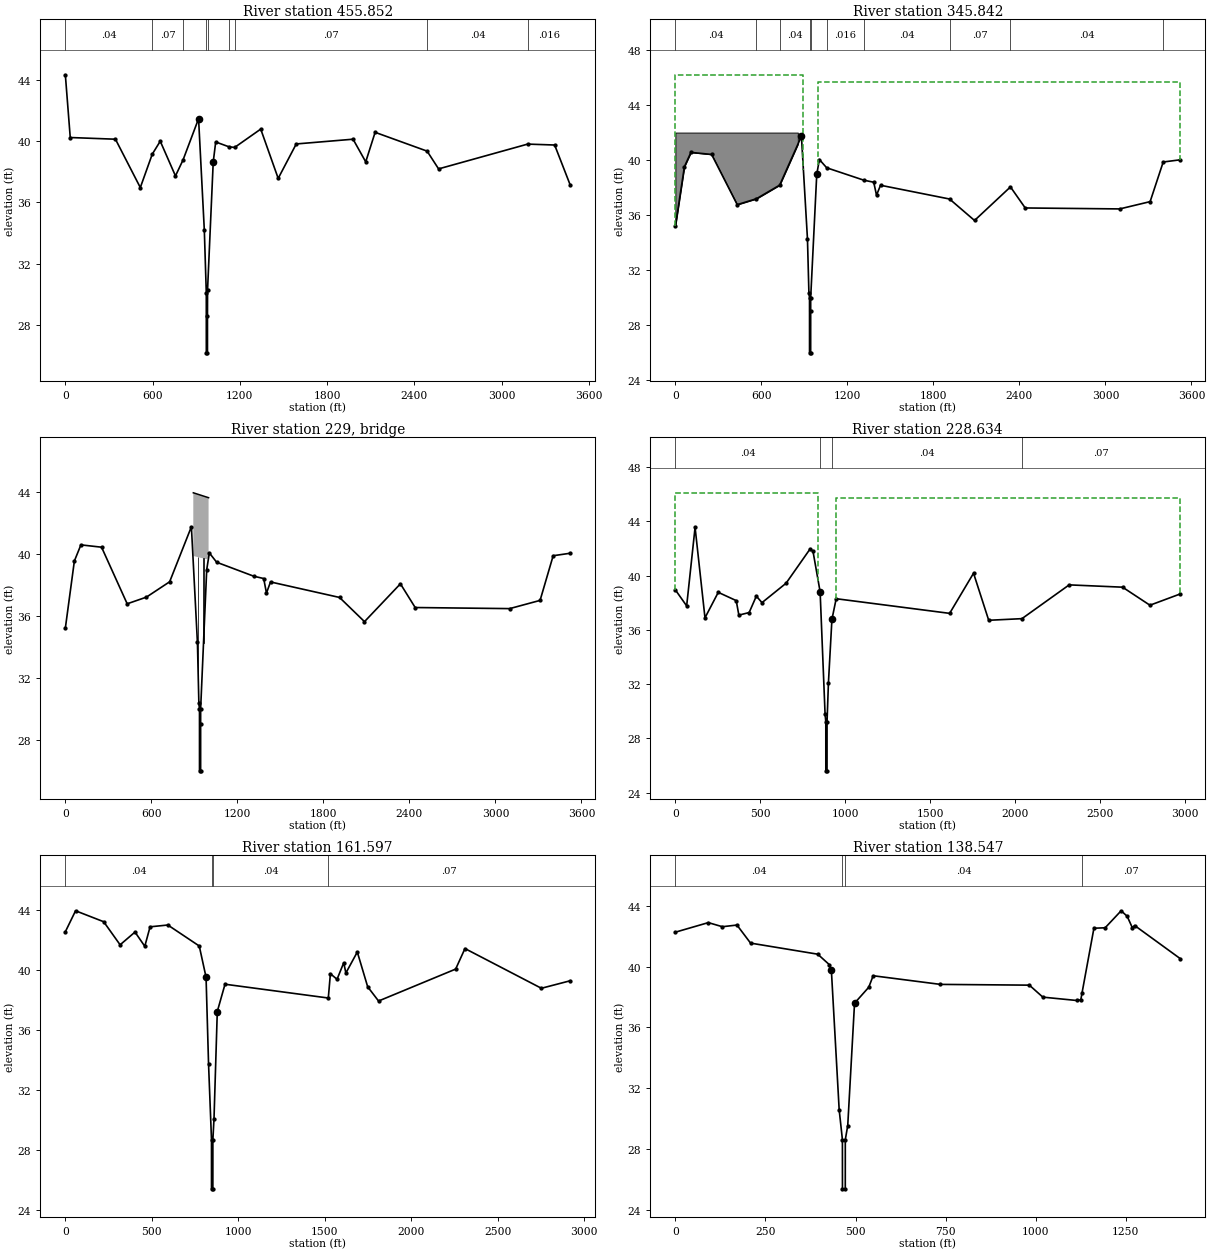
Type RM Length L Ch R = 1 ,455.852 ,80.96,110.09,135.63
BEGIN DESCRIPTION:
Bridge Section 4 - US Airport
END DESCRIPTION:
XS GIS Cut Line= 3
     3122305.442    13799885.253     3123095.755    13800094.723
      3125750.03    13800121.334
#Sta/Elev= 30
       0   44.34   33.73   40.24  344.59   40.13  515.65   36.97  597.71   39.15
   652.8      40  757.47   37.73  809.78   38.78  916.38   41.47  955.92   34.18
  969.48   30.08  969.65   26.17  977.45   26.17  977.51   28.58   978.1   30.28
 1017.09   38.63 1034.14   39.95 1123.47   39.64 1164.06   39.59 1343.82   40.79
 1463.98   37.57 1588.18   39.82  1978.9   40.13 2066.07   38.65 2130.66   40.58
 2488.22   39.35 2567.21   38.19 3179.88   39.81 3365.54   39.75 3472.01   37.15
#Mann= 9 ,-1 , 0
       0     .04       0  597.71     .07       0  809.78     .04       0
  969.48    .015       0   978.1     .04       0 1123.47    .016       0
 1164.06     .07       0 2488.22     .04       0 3179.88    .016       0
#Block Obstruct= 2 , 0
       0                 3472.01       0      40
Bank Sta=916.38,1017.09
XS Rating Curve= 0 ,0
Exp/Cntr=0.5,0.3

Type RM Length L Ch R = 1 ,345.842 ,113.63,117.2,125.09
BEGIN DESCRIPTION:
Bridge Section 3 - US Airport Rd
END DESCRIPTION:
XS GIS Cut Line= 6
     3122327.533    13800015.344     3123211.356    13800204.374
     3123304.652     13800209.22     3124421.409      13800509.7
     3125320.783    13800911.693     3125688.709    13801013.895
#Sta/Elev= 30
       0   35.19      63   39.52  108.55   40.56   252.7   40.41  431.38   36.76
  565.41   37.19  727.57   38.18  879.35   41.73  921.42   34.27   931.5   30.34
  935.82   29.99  935.95   25.99  943.76   25.99  943.83      29  943.89      30
  986.17   38.96 1004.52   40.04 1055.59   39.44 1314.23   38.54 1383.69   38.39
 1403.07   37.45  1431.2   38.17 1912.74   37.17 2086.94   35.61 2337.55   38.05
 2440.49   36.52  3099.7   36.45 3311.84   36.98 3403.08   39.86 3521.49   40.02
#Mann= 10 ,-1 , 0
       0     .04       0  565.41     .07       0  727.57     .04       0
  935.82    .015       0  943.89     .04       0 1055.59    .016       0
 1314.23     .04       0 1912.74     .07       0 2337.55     .04       0
 3403.08    .016       0
#XS Ineff= 2 , 0
       0     893    46.2     998       0    45.7
Permanent Ineff=
       F       F
#Block Obstruct= 2 , 0
       0  854.13      42 1042.47       0      42
Bank Sta=879.35,986.17
XS Rating Curve= 0 ,0
Exp/Cntr=0.5,0.3

Type RM Length L Ch R = 3 ,229     ,,,
BEGIN DESCRIPTION:
Airport Road Bridge
END DESCRIPTION:
Bridge Culvert--1,0,-1,-1, 0
Deck Dist Width WeirC Skew NumUp NumDn MinLoCord MaxHiCord MaxSubmerge Is_Ogee
0.35,116,2.6,0, 2, 2, , , 0.95, 0, 0,0,,
 892.655 999.244
  43.919  43.602
  39.843  39.606
 841.042 946.003
 43.9851 43.4868
 39.8857 39.3862
Pier Skew, UpSta & Num, DnSta & Num=  ,927.617, 2 ,877.597, 2 , 0 , 0 , 0 ,,
       2       2
 32.2265  39.843
       2       2
 32.2265  39.843
Pier Skew, UpSta & Num, DnSta & Num=  ,963.941, 2 ,912.691, 2 , 0 , 0 , 0 ,,
       2       2
 35.2365  39.843
       2       2
 35.2365  39.843
Abutment Skew #Up #Dn= , 3 , 3
 882.019 882.189     893
  41.715  45.256  46.185
  830.12 830.285   841.2
  42.152  45.228  46.237
Abutment Skew #Up #Dn= , 3 , 3
     9981009.8741010.124
  45.838  44.911  41.881
     946 956.591 956.849
  45.795  44.774  41.409
BR Coef=-1 , 1 , 1 ,1.05, 0 ,,,0.8,-1,1.2,0,
WSPro=,,,, 1 ,,,, 0 ,,,, 0 ,,,,-1 ,-1 ,-1 , 0 , 0 , 0 , 0 , 0
BC Design=,, 0 ,, 0 ,,,,,,
BC HTab HWMax=41.73
BC Use User HTab Curves=0
BC User HTab FreeFlow(D)= 0

Type RM Length L Ch R = 1 ,228.634 ,77.88,67.01,53.25
BEGIN DESCRIPTION:
Bridge Section 2 - DS Airport Rd
END DESCRIPTION:
XS GIS Cut Line= 6
     3122374.169    13800140.525     3122793.895    13800201.889
     3123200.495    13800320.655     3123282.843    13800325.941
     3124182.938    13800557.394     3125204.955    13800993.455
#Sta/Elev= 30
       0   38.94   66.39   37.76  115.93   43.55   174.2   36.88  252.37   38.76
  358.05   38.15  373.64   37.08  434.17   37.27  476.47   38.48  509.76      38
   651.4   39.43  791.32   41.93  809.63   41.81  851.96    38.8  881.02    29.8
  885.43   29.21  885.53    25.6  892.54    25.6  892.64   29.21  900.91   32.11
  921.36   36.76  946.43   38.29 1614.23   37.21 1754.95   40.17 1844.23    36.7
 2039.88   36.82 2317.83   39.31 2632.12   39.14 2793.27   37.81  2971.2   38.64
#Mann= 4 ,-1 , 0
       0     .04       0  851.96    .015       0  921.36     .04       0
 2039.88     .07       0
#XS Ineff= 2 , 0
       0  841.25    46.1     946       0    45.7
Permanent Ineff=
       F       F
Bank Sta=851.96,921.36
XS Rating Curve= 0 ,0
Exp/Cntr=0.5,0.3

Type RM Length L Ch R = 1 ,161.597 ,37.54,23.08,25.19
BEGIN DESCRIPTION:
Bridge Section 1 - DS Airport Rd
END DESCRIPTION:
XS GIS Cut Line= 6
     3122408.533    13800211.707     3123197.561    13800390.287
     3123510.321    13800398.627     3124175.455    13800580.028
     3124713.401     13800823.98     3125192.965    13801017.891
#Sta/Elev= 30
       0   42.58   59.13   43.98  221.67   43.25  316.69   41.71  402.85   42.56
  459.44   41.61  490.02   42.91  592.73   43.03  774.45   41.63  813.76   39.55
  828.28   33.73  845.24    28.7  845.25   25.43  853.08   25.43  853.16    28.7
  859.72   30.11  878.71   37.26   923.4   39.08 1520.72   38.16 1532.84   39.78
 1571.29   39.41  1609.9   40.51 1622.46   39.83 1688.47   41.23 1748.42   38.91
 1811.33   37.96 2257.16   40.09 2311.05   41.46 2753.08   38.81 2919.29   39.31
#Mann= 4 ,-1 , 0
       0     .04       0  845.24    .015       0  853.16     .04       0
 1520.72     .07       0
Bank Sta=813.76,878.71
XS Rating Curve= 0 ,0
Exp/Cntr=0.3,0.1

Type RM Length L Ch R = 1 ,138.547 ,28.86,23.81,22.77
BEGIN DESCRIPTION:
Cross-Section 4:  US of Drop Structure
END DESCRIPTION:
XS GIS Cut Line= 5
     3122770.124    13800377.777     3123185.051    13800411.138
     3123337.261    13800417.393     3123504.065    13800423.648
     3124144.179    13800605.049
#Sta/Elev= 30
       0   42.28    91.4   42.91  130.41   42.64   170.9   42.75  208.62   41.56
  395.03   40.83  426.77   40.15  432.87   39.78  454.53   30.58  463.52   28.61
  463.65   25.37  471.49   25.37  471.54   28.61  478.32   29.54  497.16    37.6
  536.58   38.65  548.87   39.41  735.53   38.84   982.3   38.79 1019.75      38
 1113.49   37.78 1125.05   37.82  1128.3   38.25 1161.48   42.54 1192.66   42.57
 1237.02   43.69  1253.7   43.33 1267.96   42.58 1274.47   42.72 1400.85   40.54
#Mann= 4 ,-1 , 0
       0     .04       0  463.52    .015       0  471.54     .04       0
  1128.3     .07       0
Bank Sta=432.87,497.16
XS Rating Curve= 0 ,0
Exp/Cntr=0.8,0.6

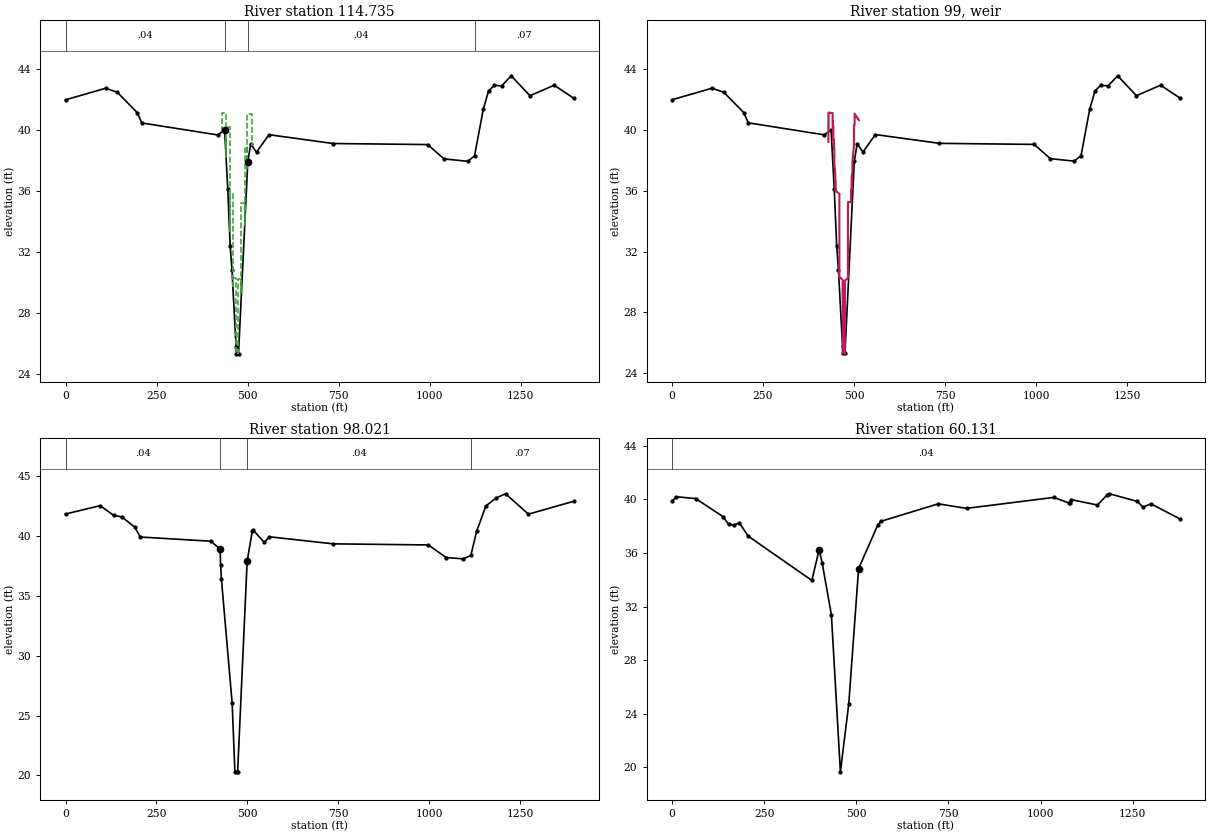
Type RM Length L Ch R = 1 ,114.735 ,17.27,16.71,16.61
BEGIN DESCRIPTION:
Cross-Section 3: Sheet Pile, Drop Structure US
END DESCRIPTION:
XS GIS Cut Line= 4
     3122764.441    13800420.343     3123133.968    13800434.043
     3123498.348    13800444.888     3124134.074    13800624.069
#Sta/Elev= 30
       0      42  109.97   42.76     142    42.5  196.84   41.16  209.58   40.48
  418.45   39.69  436.77   40.04   445.5   36.13  452.13   32.39  457.02   30.82
  468.33   25.76  468.52   25.31  474.96   25.31  500.51   37.94  508.42    39.1
  524.39   38.56  558.52   39.71  734.32   39.13  994.43   39.06    1039   38.12
 1104.31   37.96 1123.05   38.32 1146.97   41.38 1161.45   42.58  1177.5   42.96
 1197.21   42.91 1223.64   43.58 1275.13   42.27 1341.64   42.96 1394.82   42.11
#Mann= 4 ,-1 , 0
       0     .04       0  436.77    .015       0  500.51     .04       0
 1123.05     .07       0
#XS Ineff= 8 ,-1
   429.5     441   41.15     441   450.5    40.2   450.5   459.5    35.8
   459.5     469    30.3   474.5     483    30.2     483     492    35.2
     492   499.5    38.9   499.5     513    41.1
Permanent Ineff=
       F       F       F       F       F       F       F       F
Bank Sta=436.77,500.51
XS Rating Curve= 0 ,0
Exp/Cntr=0.8,0.6

Type RM Length L Ch R = 5 ,99      ,,,
BEGIN DESCRIPTION:
Drop Structure at the Confluence with Sims Bayou
END DESCRIPTION:
IW Pilot Flow=0
#Inline Weir SE= 30
 429.689   39.23 429.772  41.153 441.231  41.121 441.444  40.185 442.771  40.299
 442.957   39.34 444.376  39.388 445.847  38.583 446.008  37.706 448.896  36.959
 449.059  35.999 459.604  35.812 459.782  30.338 468.885  30.121 469.054  25.345
 474.497  25.268 474.645  30.096 483.056  30.244 483.089  35.249 491.877  35.264
  491.98  36.106 493.419  36.103  493.55  36.978  495.01  36.982 495.148  37.864
 499.486  38.939 499.599    40.3  501.17  40.309 501.264  41.086 512.901  40.657
IW Dist,WD,Coef,Skew,MaxSub,Min_El,Is_Ogee,SpillHt,DesHd
0.5,0.5,2.6,0,0.95,, 0 ,,,0,0,

Type RM Length L Ch R = 1 ,98.021  ,26.55,37.86,53.59
BEGIN DESCRIPTION:
Cross-Section 2: Sheet Pile, Drop Structure DS
END DESCRIPTION:
XS GIS Cut Line= 3
     3122765.863     13800440.33     3123501.734    13800461.411
     3124138.293    13800639.056
#Sta/Elev= 30
       0   41.82   95.56   42.52   132.1   41.71  154.88   41.58  190.18   40.73
  205.83    39.9  400.37   39.55  425.09   38.88   426.6    37.6  428.59   36.43
   458.2   26.07  465.82   20.31  472.26    20.3  473.35   20.31  499.52   37.89
  513.75   40.42  516.34   40.47  546.67   39.45  560.67   39.92  736.17   39.33
  997.53   39.24 1046.72   38.19 1093.35   38.08 1114.68   38.36 1130.41   40.37
 1155.97   42.49 1184.19   43.16 1210.04   43.51 1273.08   41.81 1397.05   42.88
#Mann= 4 ,-1 , 0
       0     .04       0  425.09    .015       0  499.52     .04       0
 1114.68     .07       0
Bank Sta=425.09,499.52
XS Rating Curve= 0 ,0
Exp/Cntr=0.8,0.6

Type RM Length L Ch R = 1 ,60.131  ,60.84,60.16,48.66
BEGIN DESCRIPTION:
Confluence of C127-00-00 and C100-00-00 (Sims Bayou)
END DESCRIPTION:
XS GIS Cut Line= 5
     3122764.711    13800473.699     3123161.181    13800476.811
     3123308.989    13800506.373     3123478.367     13800542.87
     3124116.239    13800703.423
#Sta/Elev= 30
       0   39.85   11.62    40.2   64.42   40.06  138.65   38.71  153.73   38.13
  167.23   38.09  182.97   38.25  206.59   37.26   379.5   33.95  399.23   36.25
  407.56   35.25  432.52   31.37  456.92   19.66  479.58   24.72  506.31   34.84
  558.91   38.12  567.57   38.37  722.34   39.67  799.04   39.33 1035.97   40.15
 1076.77   39.73 1078.67   39.74 1081.88   39.99 1154.11   39.58 1181.04   40.35
  1186.7   40.42 1262.47   39.85 1277.85   39.43  1299.3   39.67 1378.25   38.54
#Mann= 1 ,-1 , 0
       0     .04       0
Bank Sta=399.23,506.31
XS Rating Curve= 0 ,0
Exp/Cntr=0.3,0.1

Chan Stop Cuts=-1
Use User Specified Reach Order=0
Composite Channel Slope=5